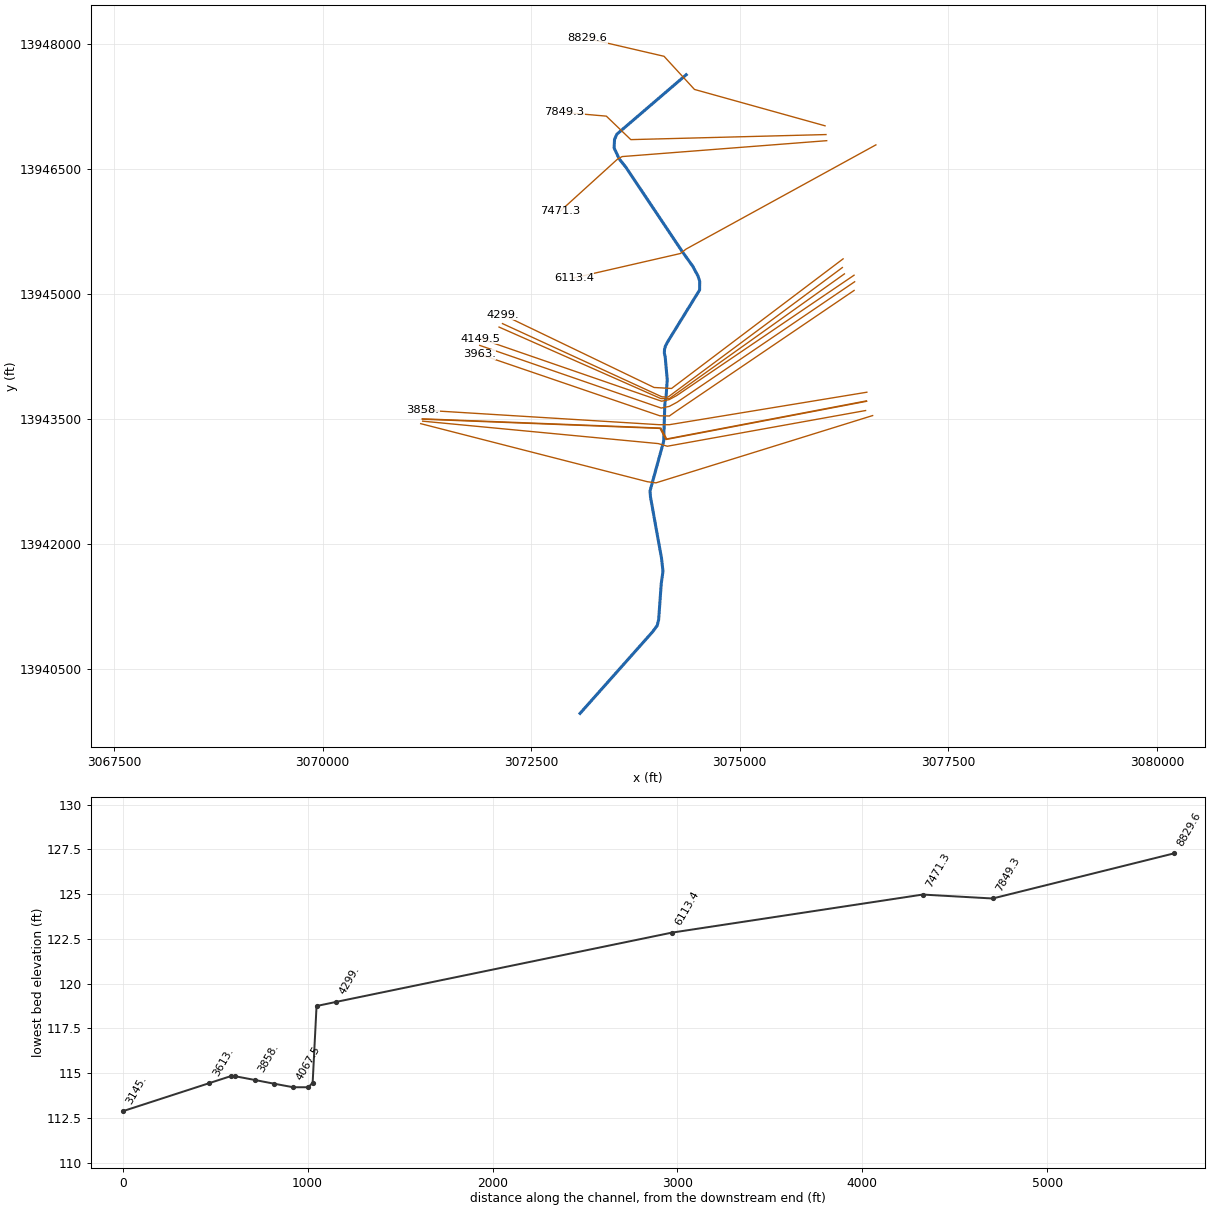
--- K131-03-00.prj (project) ---

Proj Title=K131-03-00
Current Plan=p02
Default Exp/Contr=.3,.1
English Units
Geom File=g01
Flow File=f01
Flow File=f04
Flow File=f02
Plan File=p01
Plan File=p04
Plan File=p02
Y Axis Title=Elevation
X Axis Title(PF)=Main Channel Distance
X Axis Title(XS)=Station
BEGIN DESCRIPTION:
Cypress Creek Watershed
Spring Gully Tributary 2.1
HCFCD Unit K131-03-00
Flood Hazard Model
10, 2, 1, 0.2%
Filename K131-03-00
Prepared by:  Halff Associates  DATE:  March 26, 2004
Reviewed by:  _____________________  DATE:  __________________
STATUS (Final)
END DESCRIPTION:
DSS Export Rating Curves= 0
DSS Export Rating Curve Sorted= 0
DSS Export Volume Flow Curves= 0
DXF OffsetX= 0
DXF OffsetY= 0
DXF ScaleX= 1
DXF ScaleY= 10

--- K131-03-00.p02 (plan) ---

Plan Title=Floodway
Version=Version 3.0.1  Mar 2001
Short Identifier=Floodway0607
Geom File=g01
Flow File=f02
Subcritical Flow
K Sum by GR= 0
Std Step Tol= 0.01
Critical Tol= 0.01
Num of Std Step Trials= 20
Max Error Tol= 0.3
Flow Tol Ratio= 0.001
Split Flow NTrial= 30
Split Flow Tol= 0.02
Split Flow Ratio= 0.02
Log Output Level= 0
Friction Slope Method= 1
Unsteady Friction Slope Method= 2
Parabolic Critical Depth
Global Vel Dist= 0 , 0 , 0
Global Log Level= 0
CheckData=True
Encroach Param=-1 ,0,0, 2
Encroach River=K131-03-00
Encroach Reach=Reach - 1
Encroach Node=8829.6
       1  4971.9  5025.7
Encroach Node=7849.3
       1  4969.9  5035.6
Encroach Node=7471.3
       1    4965    5037
Encroach Node=6113.4
       1  4958.8  5021.8
Encroach Node=4299.
       1 4965.98 5033.61
Encroach Node=4193.3
       1  4966.4  5034.3
Encroach Node=4182.8
       1  4966.7    5034
Encroach Node=4172.3
       1  4966.7    5034
Encroach Node=4149.5
       1  4955.4    5022
Encroach Node=4108.5
       1  4955.4    5022
Encroach Node=4067.5
       1  4955.4    5022
Encroach Node=3963.
       1 4965.09  5043.7
Encroach Node=3858.
       1  4961.4    5050
Encroach Node=3751.0
       12454.7052547.456
Encroach Node=3740.0
       12454.7052547.456
Encroach Node=3729.0
       12454.7052547.456
Encroach Node=3613.
       1  4960.8 5037.75
Encroach Node=3145.
       1 4968.38 5041.04
Encroach Node=3045.9
       1  4952.6  5041.7
Encroach Node=3035.4
       1  4952.6  5041.7
Encroach Node=3024.9
       1  4952.6  5041.7
Encroach Node=2976.2
       1  4956.9  5038.2
Encroach Node=2964.2
       1  4956.9  5038.2
Encroach Node=2952.2
       1  4956.9  5038.2
Encroach Node=2852.
       1  4956.4  5039.5
Encroach Node=1417.
       1 4967.08 5034.97
Encroach Node=1307.3
       1  4948.7    5040
Encroach Node=1245.8
       1  4948.7    5040
Encroach Node=1184.3
       1  4948.7    5040
Encroach Node=1079.
       1  4944.2  5044.2
Encroach Node=666.2
       1  4957.4    5038
Encroach Reach=K131-03-00_0007
Encroach Node=8829.6
       1  4971.9  5025.7
Encroach Node=7849.3
       1  4969.9  5035.6
Encroach Node=7471.3
       1    4965    5037
Encroach Node=6113.4
       1  4958.8  5021.8
Encroach Node=4299.
       1 4965.98 5033.61
Encroach Node=4193.3
       1  4966.4  5034.3
Encroach Node=4182.8
       1  4966.7    5034
Encroach Node=4172.3
       1  4966.7    5034
Encroach Node=4149.5
       1  4955.4    5022
Encroach Node=4108.5
       1  4955.4    5022
Encroach Node=4067.5
       1  4955.4    5022
Encroach Node=3963.
       1 4965.09  5043.7
Encroach Node=3858.
       1  4961.4    5050
Encroach Node=3751.0
       12454.7052547.456
Encroach Node=3740.0
       12454.7052547.456
Encroach Node=3729.0
       12454.7052547.456
Encroach Node=3613.
       1  4960.8 5037.75
Encroach Node=3145.
       1 4968.38 5041.04
Encroach Node=3045.9
       1  4952.6  5041.7
Encroach Node=3035.4
       1  4952.6  5041.7
Encroach Node=3024.9
       1  4952.6  5041.7
Encroach Node=2976.2
       1  4956.9  5038.2
Encroach Node=2964.2
       1  4956.9  5038.2
Encroach Node=2952.2
       1  4956.9  5038.2
Encroach Node=2852.
       1  4956.4  5039.5
Encroach Node=1417.
       1 4967.08 5034.97
Encroach Node=1307.3
       1  4948.7    5040
Encroach Node=1245.8
       1  4948.7    5040
Encroach Node=1184.3
       1  4948.7    5040
Encroach Node=1079.
       1  4944.2  5044.2
Encroach Node=666.2
       1  4957.4    5038
Computation Interval=1HOUR
Output Interval=1HOUR
Run HTab= 0
Run UNet= 0
Run PostProcess= 0
UNET Theta= 1
UNET ZTol= 0.02
UNET ZSATol= 0.1
UNET MxIter= 20
UNET MaxInSteps= 20
UNET DtIC= 0
UNET DtMin= 0
UNET MaxCRTS= 20
UNET WFStab= 2
UNET SFStab= 1
UNET WFX= 1
UNET SFX= 1
UNET Convert EG Bridges=-1
UNET Use Existing IB Tables=-1
Instantaneous Interval=1HOUR
Write IC File= 0
Write Velocity= 0
Write Detailed= 0

--- K131-03-00.p01 (plan) ---

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Plan Title=FEMA Effective June 2007
Short Identifier=FEMAeff0607
Geom File=g01
Flow File=f01
Encroach Param=-1 ,0,0, 0

--- K131-03-00.p04 (plan) ---

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Plan Title=Storage Routing
Short Identifier=Store_Rout
Geom File=g01
Flow File=f04
Encroach Param=-1 ,0,0, 0

--- K131-03-00.f02 (steady flow) ---

Flow Title=Floodway
Version=Version 3.0.1  Mar 2001
Number of Profiles= 2
Profile Names=1PCT_100yr, 1PCTFloodway_100yrFW
River Rch & RM=K131-03-00,K131-03-00_0007,8829.6
     690     690
River Rch & RM=K131-03-00,K131-03-00_0007,7849.3
     700     700
River Rch & RM=K131-03-00,K131-03-00_0007,7471.3
     760     760
River Rch & RM=K131-03-00,K131-03-00_0007,6113.4
     850     850
River Rch & RM=K131-03-00,K131-03-00_0007,4193.3
    1000    1000
River Rch & RM=K131-03-00,K131-03-00_0007,3751.0
    1070    1070
River Rch & RM=K131-03-00,K131-03-00_0007,2976.2
    1240    1240
River Rch & RM=K131-03-00,K131-03-00_0007,1307.3
    1300    1300
Boundary for River Rch & Prof#=K131-03-00,K131-03-00_0007, 1
Up Type= 0
Dn Type= 3
Dn Slope=.0029
Boundary for River Rch & Prof#=K131-03-00,K131-03-00_0007, 2
Up Type= 0
Dn Type= 3
Dn Slope=.0029
DSS Import GetInterval= 0
DSS Import GetPeak= 0
DSS Import FillOption= 0

--- K131-03-00.f01 (steady flow) ---

Flow Title=FEMA Effective June 2007
Version=Version 3.0.1  Mar 2001
Number of Profiles= 4
Profile Names=10PCT_10yr, 2PCT_50yr, 1PCT_100yr, 0.2PCT_500yr
River Rch & RM=K131-03-00,K131-03-00_0007,8829.6
     390     570     690     980
River Rch & RM=K131-03-00,K131-03-00_0007,7849.3
     400     580     700    1010
River Rch & RM=K131-03-00,K131-03-00_0007,7471.3
     440     630     760    1120
River Rch & RM=K131-03-00,K131-03-00_0007,6113.4
     490     700     850    1300
River Rch & RM=K131-03-00,K131-03-00_0007,4193.3
     550     820    1000    1390
River Rch & RM=K131-03-00,K131-03-00_0007,3751.0
     590     870    1070    1490
River Rch & RM=K131-03-00,K131-03-00_0007,2976.2
     670    1010    1240    1720
River Rch & RM=K131-03-00,K131-03-00_0007,1307.3
     700    1050    1300    1800
Boundary for River Rch & Prof#=K131-03-00,K131-03-00_0007, 1
Up Type= 0
Dn Type= 3
Dn Slope=.0029
Boundary for River Rch & Prof#=K131-03-00,K131-03-00_0007, 2
Up Type= 0
Dn Type= 3
Dn Slope=.0029
Boundary for River Rch & Prof#=K131-03-00,K131-03-00_0007, 3
Up Type= 0
Dn Type= 3
Dn Slope=.0029
Boundary for River Rch & Prof#=K131-03-00,K131-03-00_0007, 4
Up Type= 0
Dn Type= 3
Dn Slope=.0029
DSS Import GetInterval= 0
DSS Import GetPeak= 0
DSS Import FillOption= 0

--- K131-03-00.f04 (steady flow) ---

Flow Title=Storage Routing
Version=Version 3.0.1  Mar 2001
Number of Profiles= 7
Profile Names=0.25*10% flood, 0.50*10%flood, 10% flood, 2% flood, 1% flood, 0.2%flood, 1.25*0.2% flood
River Rch & RM=K131-03-00,K131-03-00_0007,8829.6
      46      93     185     252     270     338     423
River Rch & RM=K131-03-00,K131-03-00_0007,7849.3
      54     108     215     285     310     380     475
River Rch & RM=K131-03-00,K131-03-00_0007,6113.4
      69     138     276     366     400     492     615
River Rch & RM=K131-03-00,K131-03-00_0007,4193.3
      94     187     374     496     543     671     839
River Rch & RM=K131-03-00,K131-03-00_0007,4149.5
     115     230     460     610     670     830    1038
River Rch & RM=K131-03-00,K131-03-00_0007,3751
     121     242     484     642     705     873    1091
River Rch & RM=K131-03-00,K131-03-00_0007,3045.9
     134     268     535     711     779     965    1206
River Rch & RM=K131-03-00,K131-03-00_0007,2976.2
     152     303     606     807     882    1093    1366
River Rch & RM=K131-03-00,K131-03-00_0007,1245.8
     165     330     660     880     960    1190    1488
River Rch & RM=K131-03-00,K131-03-00_0007,666.2
     182     363     726     966    1093    1350    1688
Boundary for River Rch & Prof#=K131-03-00,K131-03-00_0007, 1
Up Type= 0
Dn Type= 3
Dn Slope=.0029
Boundary for River Rch & Prof#=K131-03-00,K131-03-00_0007, 2
Up Type= 0
Dn Type= 3
Dn Slope=.0029
Boundary for River Rch & Prof#=K131-03-00,K131-03-00_0007, 3
Up Type= 0
Dn Type= 3
Dn Slope=.0029
Boundary for River Rch & Prof#=K131-03-00,K131-03-00_0007, 4
Up Type= 0
Dn Type= 3
Dn Slope=.0029
Boundary for River Rch & Prof#=K131-03-00,K131-03-00_0007, 5
Up Type= 0
Dn Type= 3
Dn Slope=.0029
Boundary for River Rch & Prof#=K131-03-00,K131-03-00_0007, 6
Up Type= 0
Dn Type= 3
Dn Slope=.0029
Boundary for River Rch & Prof#=K131-03-00,K131-03-00_0007, 7
Up Type= 0
Dn Type= 3
Dn Slope=.0029
DSS Import GetInterval= 0
DSS Import GetPeak= 0
DSS Import FillOption= 0

--- K131-03-00.g01 (geometry) ---

Geom Title=K131-03-00 June 2007
Version=Version 3.0.1  Mar 2001

River Reach=K131-03-00      ,K131-03-00_0007
Reach XY= 30
      3074358.08     13947636.64      3073526.85     13946922.31
      3073499.07     13946859.81        3073494.       13946758.
      3073554.21     13946626.97      3073634.49     13946526.48
      3074316.37     13945504.36       3074435.5       13945338.
       3074499.5       13945219.        3074520.       13945155.
       3074518.5       13945051.      3074140.75       13944437.
        3074109.       13944378.        3074098.       13944337.
      3074096.29     13944292.97      3074106.25       13944248.
      3074130.75       13943972.      3074116.27     13943760.72
      3074105.14     13943715.01      3074100.63     13943644.53
      3074088.25       13943235.      3073924.27     13942637.33
      3073929.85     13942565.48      3074061.75       13941832.
      3074079.75       13941673.      3074058.97     13941525.61
      3074027.72     13941090.71      3074010.36      13941020.4
      3073953.49     13940943.84        3073086.       13939966.

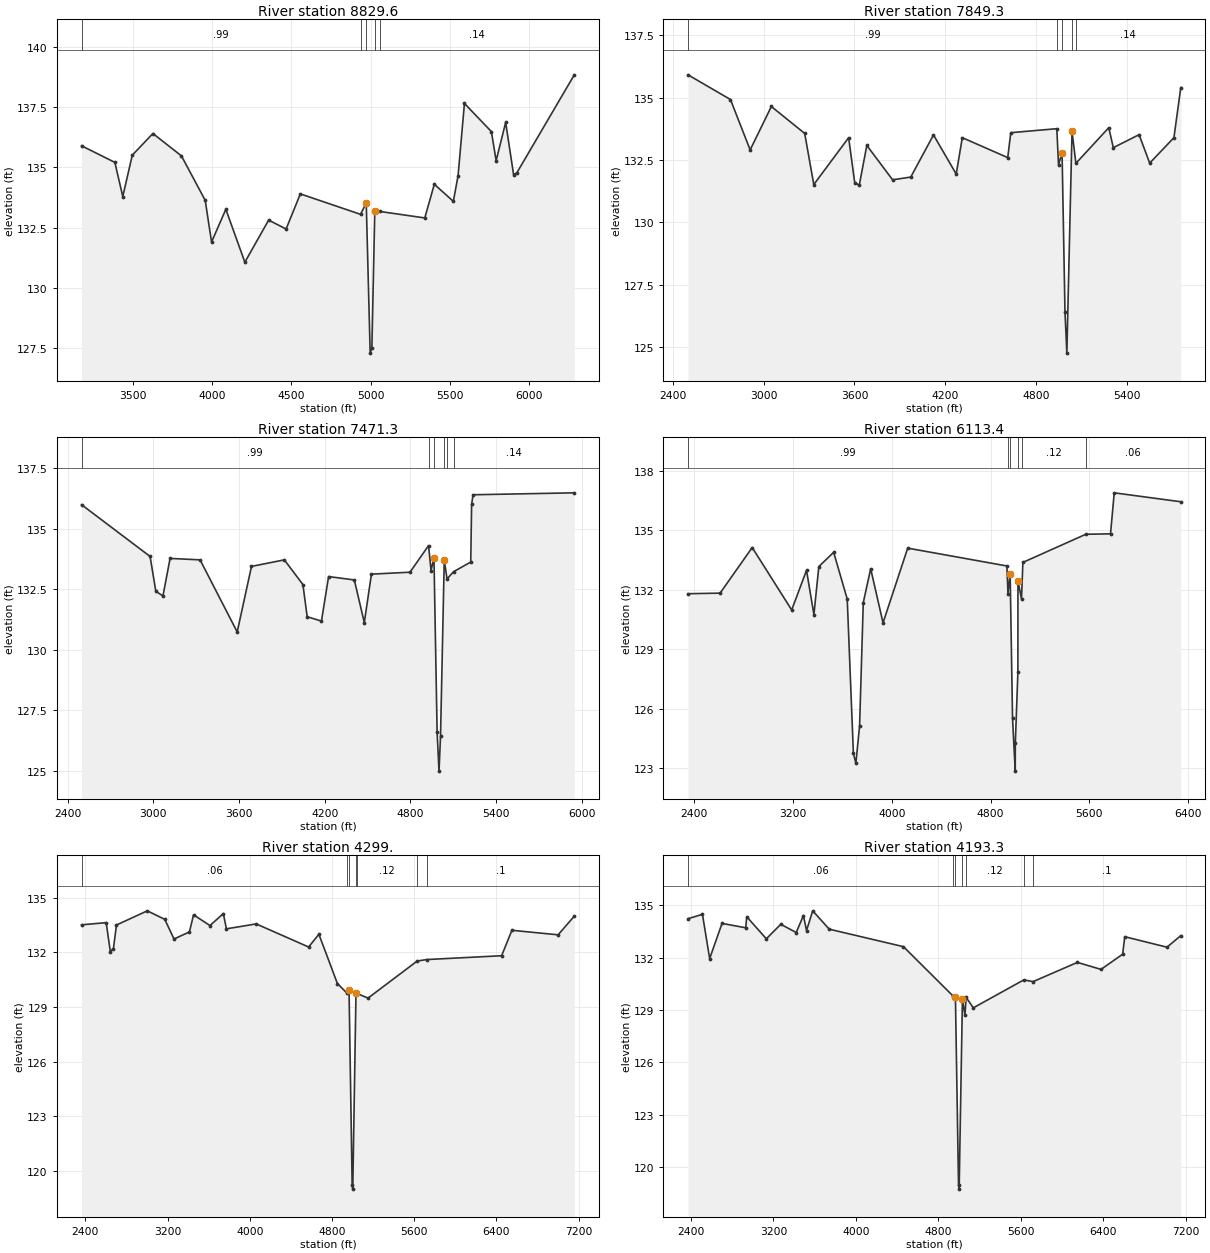
Type RM Length L Ch R = 1 ,8829.6  ,979,980.3,982
BEGIN DESCRIPTION:
Cross Section K131-03-00-X5
END DESCRIPTION:
XS GIS Cut Line= 5
      3076022.25     13947023.18      3074457.27     13947460.05
       3074092.3     13947858.21      3073213.04     13948062.81
      3073174.33     13948073.87
#Sta/Elev= 30
  3176.2   135.9  3386.2  135.21  3436.2  133.79  3496.2  135.51  3626.2  136.41
  3806.2  135.48  3956.2  133.63  3996.2   131.9  4086.2  133.26  4206.2  131.06
  4356.2  132.81  4466.2  132.44  4556.2   133.9  4935.6  133.05  4971.9  133.52
  4996.6  127.28  5007.4  127.51  5025.7  133.17    5057  133.17  5341.1   132.9
  5401.1   134.3  5521.1  133.59  5551.1  134.66  5591.1  137.66  5761.1  136.49
  5791.1  135.28  5851.1  136.87  5901.1   134.7  5921.1  134.77  6284.1  138.85
#Mann= 5 ,-1 , 0
  3176.2     .99       0  4935.6    .045       0  4971.9     .04       0
  5025.7    .045       0    5057     .14       0
Bank Sta=4971.9,5025.7
XS Rating Curve= 0
Exp/Cntr=.3,.1

Type RM Length L Ch R = 1 ,7849.3  ,327.9,378,427.1
BEGIN DESCRIPTION:
Cross Section K131-03-00-X4
END DESCRIPTION:
XS GIS Cut Line= 4
      3076033.31     13946918.12      3073694.14     13946857.29
      3073401.06     13947139.31      3072897.83     13947183.55
#Sta/Elev= 30
  2501.4  135.92  2781.4  134.93  2911.4  132.91  3051.4  134.65  3271.4  133.57
  3331.4  131.52  3561.4   133.4  3601.4   131.6  3631.4  131.49  3681.4  133.09
  3851.4  131.71  3971.4  131.82  4121.4  133.51  4271.4  131.94  4311.4   133.4
  4611.4   132.6  4631.4   133.6  4935.2  133.76  4946.4  132.31  4969.9   132.8
  4989.2  126.39  5001.5  124.76  5035.6  133.66    5061  132.37  5278.1   133.8
  5308.1     133  5478.1  133.52  5548.1  132.38  5708.1   133.4  5753.3  135.41
#Mann= 5 ,-1 , 0
  2501.4     .99       0  4935.2    .045       0  4969.9     .04       0
  5035.6    .045       0    5061     .14       0
Bank Sta=4969.9,5035.6
XS Rating Curve= 0
Exp/Cntr=.3,.1

Type RM Length L Ch R = 1 ,7471.3  ,1351.7,1357.9,1358.6
BEGIN DESCRIPTION:
Cross Section K131-03-00-X3
END DESCRIPTION:
XS GIS Cut Line= 4
       3076041.8     13946844.66      3073590.76     13946653.76
      3073535.41     13946623.64      3072848.22     13945998.31
#Sta/Elev= 30
  2497.2  135.99  2977.2  133.85  3017.2  132.41  3067.2  132.22  3117.2  133.77
  3327.2  133.71  3587.2  130.73  3687.2  133.44  3917.2  133.71  4047.2  132.69
  4077.2  131.36  4177.2  131.18  4227.2  133.02  4407.2  132.88  4477.2  131.12
  4527.2  133.12  4797.2   133.2  4927.2   134.3  4944.6  133.27    4965   133.8
  4987.1  126.59  5000.4  124.98  5011.1  126.44    5037   133.7  5056.6  132.92
  5101.9  133.22  5222.6  133.62  5228.7     136  5238.7   136.4  5947.8  136.48
#Mann= 6 ,-1 , 0
  2497.2     .99       0  4927.2    .045       0    4965     .04       0
    5037    .045       0  5056.6     .07       0  5101.9     .14       0
Bank Sta=4965,5037
XS Rating Curve= 0
Exp/Cntr=.3,.1

Type RM Length L Ch R = 1 ,6113.4  ,1899.9,1814.4,1780
BEGIN DESCRIPTION:
Cross Section K131-03-00-X02; N-values on left represents future residential area
END DESCRIPTION:
XS GIS Cut Line= 4
      3076631.42     13946794.21      3074357.31      13945543.2
      3074288.03     13945489.32      3073012.02      13945196.1
#Sta/Elev= 30
  2348.7   131.8  2608.7  131.83  2868.7  134.13  3188.7  130.98  3308.7  132.98
  3368.7  130.75  3408.7  133.17  3528.7  133.89  3638.7  131.53  3688.7  123.74
  3708.7  123.25  3738.7  125.12  3768.7  131.35  3828.7  133.06  3928.7  130.33
  4128.7   134.1  4932.3   133.2    4941  131.81  4958.8   132.8    4978  125.51
  4999.9  122.85  5000.6  124.25  5021.4  127.83  5021.8  132.45  5050.7  131.54
  5061.9  133.38    5572   134.8    5772  134.82    5802  136.89  6341.2  136.44
#Mann= 6 ,-1 , 0
  2348.7     .99       0    4941    .045       0  4958.8    .045       0
  5021.8    .045       0  5050.7     .12       0    5572     .06       0
Bank Sta=4958.8,5021.8
XS Rating Curve= 0
Exp/Cntr=.3,.1

Type RM Length L Ch R = 1 ,4299.   ,92.5,105.7,106.8
BEGIN DESCRIPTION:
K131-03-00-S02C_WEIR- US - XS 4
END DESCRIPTION:
XS GIS Cut Line= 4
      3076238.43      13945425.2       3074182.2     13943868.37
      3073973.19     13943880.32      3072164.89     13944751.98
#Sta/Elev= 30
  2362.6  133.52  2602.6  133.64  2642.6  132.05  2672.6  132.21  2702.6  133.51
  3002.6  134.29  3172.6  133.82  3262.6  132.74  3412.6  133.13  3452.6  134.07
  3612.6  133.48  3742.6  134.14  3772.6   133.3  4062.6  133.57  4572.6   132.3
  4672.6     133  4852.6  130.29 4948.28  129.75 4965.98  129.93 4996.21  119.23
 5002.36  118.98 5033.61  129.76    5043  129.74  5151.1  129.49    5630  131.53
    5724  131.61  6451.1  131.82  6551.1  133.22  7001.1  132.97  7158.5     134
#Mann= 7 ,-1 , 0
  2362.6     .06       0 4948.28    .045       0 4965.98     .04       0
 5033.61    .045       0    5043     .12       0    5630     .06       0
    5724      .1       0
Bank Sta=4965.98,5033.61
XS Rating Curve= 0
Exp/Cntr=.7,.5

Type RM Length L Ch R = 1 ,4193.3  ,32.9,21,20
BEGIN DESCRIPTION:
Upstream Section of Bridge/Culvert/Weir
END DESCRIPTION:
XS GIS Cut Line= 6
      3076229.72     13945320.76      3074370.64     13943936.79
      3074139.71     13943764.88      3074073.53     13943767.64
       3074067.2      13943767.9      3072156.18     13944647.51
#Sta/Elev= 30
  2371.4  134.22  2511.4  134.47  2581.4  131.94  2701.4  133.95  2931.4   133.7
  2941.4  134.33  3131.4  133.07  3271.4   133.9  3421.4  133.43  3491.4   134.4
  3521.4  133.54  3581.4  134.67  3741.9  133.62  4461.9  132.62  4939.6  129.82
  4966.4  129.76  4996.4  119.01  5002.5  118.75  5034.3   129.6  5058.7   128.7
    5070  129.72    5140  129.12    5630  130.72    5720  130.62    6150  131.72
  6379.5  131.32  6589.5  132.19  6609.5  133.19  7019.5  132.59  7153.3  133.25
#Mann= 7 ,-1 , 0
  2371.4     .06       0  4939.6    .045       0  4966.4     .02       0
  5034.3    .045       0    5070     .12       0    5630     .06       0
    5720      .1       0
#XS Ineff= 2 , 0
       0  4956.4  129.59  5044.3       0  128.68
Permanent Ineff=
       F       F
Bank Sta=4966.4,5034.3
XS Rating Curve= 0
Exp/Cntr=.7,.5

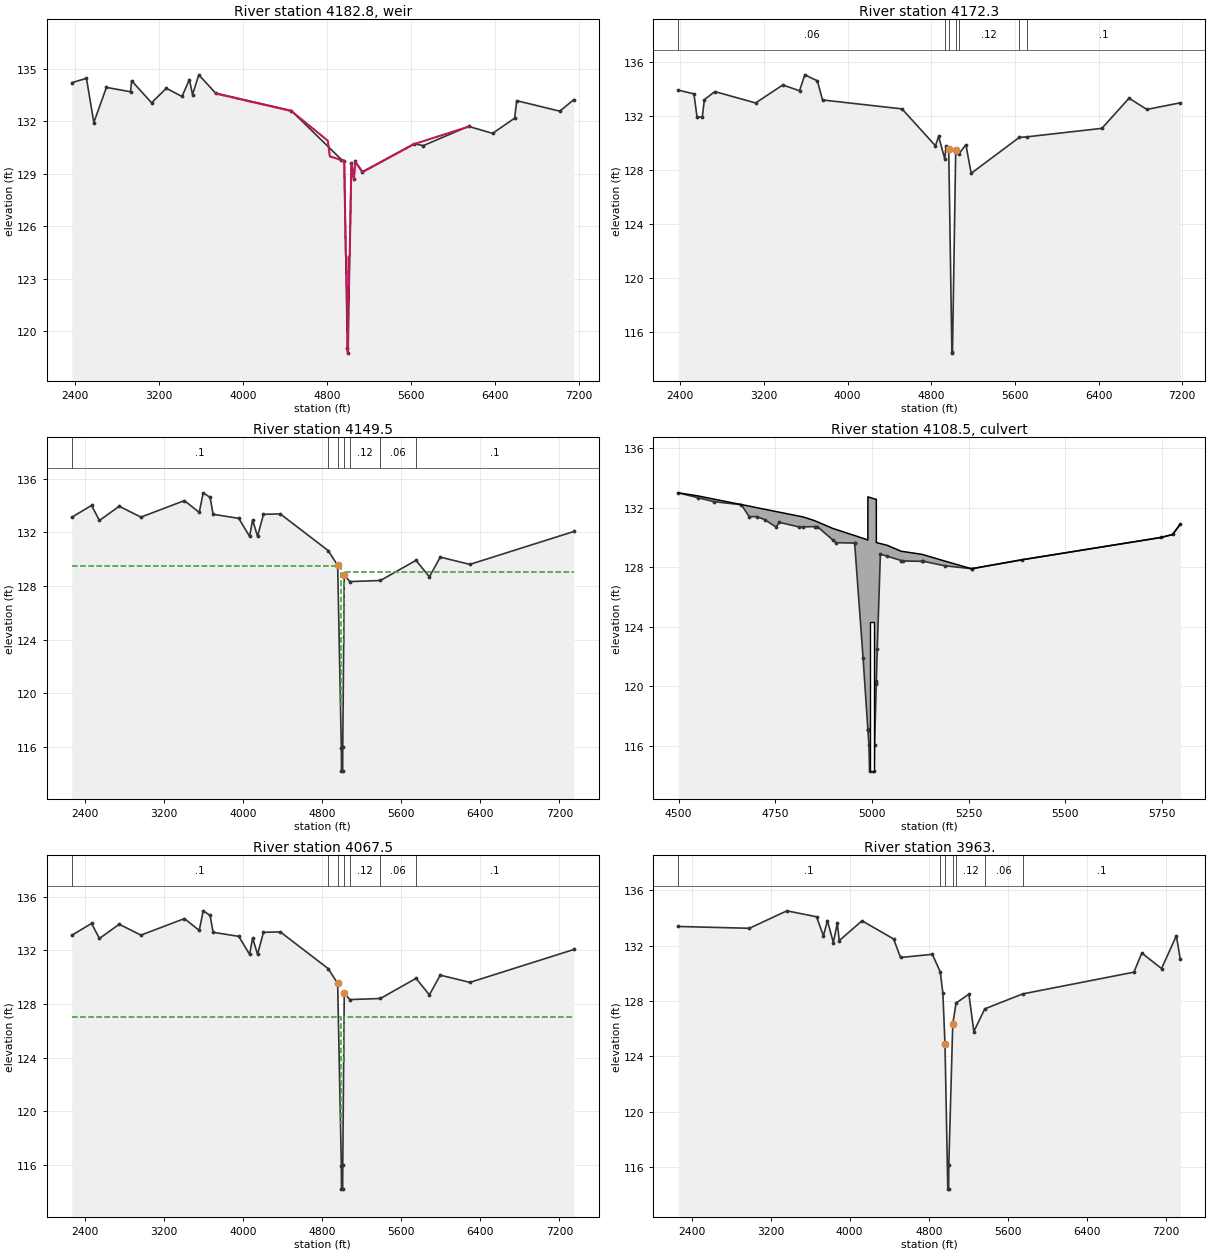
Type RM Length L Ch R = 5 ,4182.8  ,,,
BEGIN DESCRIPTION:
WIER 40' US SPRING CYPRESS
Structure ID: K131-03-00-S02C
END DESCRIPTION:
IW Pilot Flow=0
#Inline Weir SE= 30
  3741.9   133.6  4461.9   132.6  4809.6   130.9  4829.6     130  4966.4  129.74
 4981.64  124.28  4987.1  124.28  4987.2  123.41 4988.98  123.41  4989.1  122.55
  4992.1  122.55  4992.2  121.64    4997  121.67  4997.3  118.77  5002.5  118.74
 5002.79  118.78    5003  121.66  5007.8  121.63  5007.9  122.55  5010.9  122.56
    5011  123.51  5012.6  123.51  5012.7  124.25 5018.45  124.31  5034.3  129.59
  5058.7  128.68    5070   129.7    5140   129.1    5630   130.7    6150   131.7
IW Dist,WD,Coef,Skew,MaxSub,Min_El,Is_Ogee,SpillHt,DesHd
10,1,3,0,.95,, 0 ,,,0,0,

Type RM Length L Ch R = 1 ,4172.3  ,12.8,22.8,32.4
BEGIN DESCRIPTION:
Cross Section FIELD_DS
Located At: WIER 40' US SPRING CYPRESS
END DESCRIPTION:
XS GIS Cut Line= 4
      3076254.34     13945244.67      3074152.91     13943744.98
      3074053.26     13943747.51      3072114.93     13944606.01
#Sta/Elev= 30
  2380.2  133.93  2530.2  133.65  2560.2  131.93  2610.2  131.93  2630.2  133.22
  2730.2  133.82  3120.2  132.98  3380.2  134.31  3540.2  133.88  3590.2  135.06
  3710.2  134.62  3760.2   133.2    4520  132.54    4840  129.81    4870   130.5
    4930  128.82    4940   129.8  4966.7  129.59  4997.1  114.56  5002.7  114.47
    5034  129.51  5061.4  129.18  5131.4  129.89  5181.4  127.77  5641.4  130.43
  5711.4  130.47  6431.4   131.1  6691.4  133.33  6861.6   132.5  7181.5  132.99
#Mann= 7 ,-1 , 0
  2380.2     .06       0    4930    .045       0  4966.7     .02       0
    5034    .045       0  5061.4     .12       0  5641.4     .06       0
  5711.4      .1       0
Bank Sta=4966.7,5034
XS Rating Curve= 0
Exp/Cntr=.7,.5

Type RM Length L Ch R = 1 ,4149.5  ,85.7,82,80
BEGIN DESCRIPTION:
Upstream Section of Bridge/Culvert/Weir
END DESCRIPTION:
XS GIS Cut Line= 5
      3076369.56      13945228.6      3074243.41     13943782.85
       3074152.1     13943733.68       3074063.2     13943715.47
      3071893.27     13944466.62
#Sta/Elev= 30
  2264.5  133.12  2464.5     134  2544.5  132.88  2744.5  133.942964.501  133.13
  3404.5  134.36  3554.5  133.48  3594.5  134.94  3664.5   134.6  3694.5  133.34
  3954.5  133.04  4064.5  131.69  4094.5  132.92  4144.5   131.7  4204.5  133.34
4374.502  133.37    4859  130.644955.402  129.53  4992.4  115.95    4994  114.21
    5006  114.215006.899  115.98    5022  128.79  5079.7  128.335388.002  128.41
5748.001  129.91  5883.5  128.68  5993.5  130.15  6293.5  129.617345.302  132.06
#Mann= 7 ,-1 , 0
  2264.5      .1       0    4859    .045       04955.402     .02       0
    5022    .045       0  5079.7     .12       05388.002     .06       0
5748.001      .1       0
#XS Ineff= 2 , 0
       0    4984  129.47    5016       0  129.07
Permanent Ineff=
       F       F
Bank Sta=4955.402,5022
XS Rating Curve= 0
Exp/Cntr=.5,.3

Type RM Length L Ch R = 2 ,4108.5  ,,,
BEGIN DESCRIPTION:
SPRING CYPRESS; Roadway width around 30' but headwall to headwall is closer to 60' VRR
Structure ID: K131-03-00-S02
END DESCRIPTION:
Bridge Culvert--1,0,-1,-1, 0
Deck Dist Width WeirC Skew NumUp NumDn MinLoCord MaxHiCord MaxSubmerge Is_Ogee
10,62,3,0, 43, 43, , , .95, 0, ,,,
    4499    4549  4592.44662.398  4682.4  4702.4  4722.4  4752.4  4760.34812.402
4822.102  4851.9    48594898.602  4906.84955.2024955.402  4977.3 4989.59  4989.7
4989.812  4992.4    4994  5002.7    50065006.899 5011.39  5011.5 5011.615014.002
    50225039.902  5076.1  5079.75128.702  5133.2    5188 5257.755258.0015388.002
5748.001    5778    5798
     133   132.8  132.57  132.21  132.11     132   131.9  131.74   131.7  131.43
  131.38  131.13  131.05  130.61  130.54  130.13  130.13  129.94  129.83  132.73
  132.73  132.71  132.69  132.62   132.6  132.59  132.56  132.56  129.66  129.64
  129.59  129.47  129.07  129.06  128.87  128.84  128.42   127.9   127.9   128.5
     130   130.2   130.9
     133  132.68   132.4   132.2   131.4   131.4   131.2   130.7  131.02   130.7
  130.71  130.73  130.73  129.84  129.65  129.62  129.62  121.87  117.12  117.08
  117.04  116.04   114.3   114.3   114.3  116.07  120.15  120.25  120.35  122.52
  128.88  128.74  128.45  128.42   128.4   128.4   128.1   127.9   127.9   128.5
     130   130.2   130.9
    4499    4549  4592.44662.398  4682.4  4702.4  4722.4  4752.4  4760.34812.402
4822.102  4851.9    48594898.602  4906.84955.2024955.402  4977.3 4989.59  4989.7
4989.812  4992.4    4994  5002.7    50065006.899 5011.39  5011.5 5011.615014.002
    50225039.902  5076.1  5079.75128.702  5133.2    5188 5257.755258.0015388.002
5748.001    5778    5798
     133   132.8  132.57  132.21  132.11     132   131.9  131.74   131.7  131.43
  131.38  131.13  131.05  130.61  130.54  130.13  130.13  129.94  129.83  132.73
  132.73  132.71  132.69  132.62   132.6  132.59  132.56  132.56  129.66  129.64
  129.59  129.47  129.07  129.06  128.87  128.84  128.42   127.9   127.9   128.5
     130   130.2   130.9
  132.89  132.57  132.29  132.09  131.29  131.29  131.09  130.59  130.91  130.59
   130.6  130.62  130.62  129.73  129.54  129.51  129.51  121.76  117.01  116.97
  116.93  115.93  114.19  114.19  114.19  115.96  120.04  120.14  120.24  122.41
  128.77  128.63  128.34  128.31  128.29  128.29  127.99  127.79  127.79  128.39
  129.89  130.09  130.79
BR Coef= 1 , 1 , 0 ,1.25, 0 ,,,.8,-1,2,0,
WSPro=,,,, 1 ,,,, 0 ,,,, 0 ,,,,-1 ,-1 ,-1 , 0 , 0 , 0 , 0 , 0
Culvert=2,10,12,62,.015,.5,1,8,3,114.3,5000,114.19,5000,Culvert #1  , 0 ,10
Culvert Bottom n=.015
BR U #Sta/Elev= 43
    4499     133    4549  132.68  4592.4   132.4  4662.4   132.2  4682.4   131.4
  4702.4   131.4  4722.4   131.2  4752.4   130.7  4760.3  131.02  4812.4   130.7
  4822.1  130.71  4851.9  130.73    4859  130.73  4898.6  129.84  4906.8  129.65
  4955.2  129.62  4955.4  129.62  4977.3  121.87 4989.59  117.12  4989.7  117.08
 4989.81  117.04  4992.4  116.04    4994   114.3  5002.7   114.3    5006   114.3
  5006.9  116.07 5011.39  120.15  5011.5  120.25 5011.61  120.35    5014  122.52
    5022  128.88  5039.9  128.74  5076.1  128.45  5079.7  128.42  5128.7   128.4
  5133.2   128.4    5188   128.1 5257.75   127.9    5258   127.9    5388   128.5
    5748     130    5778   130.2    5798   130.9
BR U #Mann= 7
    4499      .1    4859    .045  4955.4     .02    5022    .045  5079.7     .12
    5388     .06    5748      .1
BR U Banks=4955.4,5022
BR D #Sta/Elev= 43
    4499  132.89    4549  132.57  4592.4  132.29  4662.4  132.09  4682.4  131.29
  4702.4  131.29  4722.4  131.09  4752.4  130.59  4760.3  130.91  4812.4  130.59
  4822.1   130.6  4851.9  130.62    4859  130.62  4898.6  129.73  4906.8  129.54
  4955.2  129.51  4955.4  129.51  4977.3  121.76 4989.59  117.01  4989.7  116.97
 4989.81  116.93  4992.4  115.93    4994  114.19  5002.7  114.19    5006  114.19
  5006.9  115.96 5011.39  120.04  5011.5  120.14 5011.61  120.24    5014  122.41
    5022  128.77  5039.9  128.63  5076.1  128.34  5079.7  128.31  5128.7  128.29
  5133.2  128.29    5188  127.99 5257.75  127.79    5258  127.79    5388  128.39
    5748  129.89    5778  130.09    5798  130.79
BR D #Mann= 7
    4499      .1    4859    .045  4955.4     .02    5022    .045  5079.7     .12
    5388     .06    5748      .1
BR D Banks=4955.4,5022
BC Design=,, 0 ,, 0 ,,,,,,

Type RM Length L Ch R = 1 ,4067.5  ,111,104.5,95.6
BEGIN DESCRIPTION:
Downstream Section of Bridge/Culvert/Weir
END DESCRIPTION:
XS GIS Cut Line= 5
      3076377.01     13945150.34      3074250.01     13943704.01
       3074155.2     13943652.96      3074058.04     13943633.06
      3071882.93       13944386.
#Sta/Elev= 30
  2264.5  133.12  2464.5     134  2544.5  132.88  2744.5  133.942964.501  133.13
  3404.5  134.36  3554.5  133.48  3594.5  134.94  3664.5   134.6  3694.5  133.34
  3954.5  133.04  4064.5  131.69  4094.5  132.92  4144.5   131.7  4204.5  133.34
4374.502  133.37    4859  130.644955.402  129.53  4992.4  115.95    4994  114.21
    5006  114.215006.899  115.98    5022  128.79  5079.7  128.335388.002  128.41
5748.001  129.91  5883.5  128.68  5993.5  130.15  6293.5  129.617345.302  132.06
#Mann= 7 ,-1 , 0
  2264.5      .1       0    4859    .045       04955.402     .02       0
    5022    .045       0  5079.7     .12       05388.002     .06       0
5748.001      .1       0
#XS Ineff= 2 , 0
       0    4984     127    5016       0     127
Permanent Ineff=
       F       F
Bank Sta=4955.402,5022
XS Rating Curve= 0
Exp/Cntr=.5,.3

Type RM Length L Ch R = 1 ,3963.   ,104,105,106.4
BEGIN DESCRIPTION:
K131-03-00-S02_SPRING CYPRESS - DS - XS 1
END DESCRIPTION:
XS GIS Cut Line= 5
       3076370.4      13945045.8      3074243.48     13943599.53
      3074156.26     13943537.96      3074042.76     13943539.95
       3071876.4     13944281.53
#Sta/Elev= 30
  2264.8  133.38  2984.8  133.25  3364.8  134.51  3664.8  134.08  3734.8   132.7
  3774.8  133.81  3834.8  132.22  3874.8  133.62  3894.8  132.36  4124.8  133.79
  4444.8  132.48  4514.8  131.14    4837  131.37    4917   130.1  4943.7  128.55
 4965.09  124.87 4993.47  114.41  5001.5  114.41 5003.83  116.17  5043.7  126.35
  5077.2  127.85  5207.2  128.49  5257.2  125.79  5367.2  127.43    5752  128.51
  6877.2  130.08  6957.2  131.46  7157.2  130.34  7307.2  132.71    7347     131
#Mann= 7 ,-1 , 0
  2264.8      .1       0    4917    .045       0 4965.09     .04       0
  5043.7    .045       0  5077.2     .12       0  5367.2     .06       0
    5752      .1       0
Bank Sta=4965.09,5043.7
XS Rating Curve= 0
Exp/Cntr=.3,.1

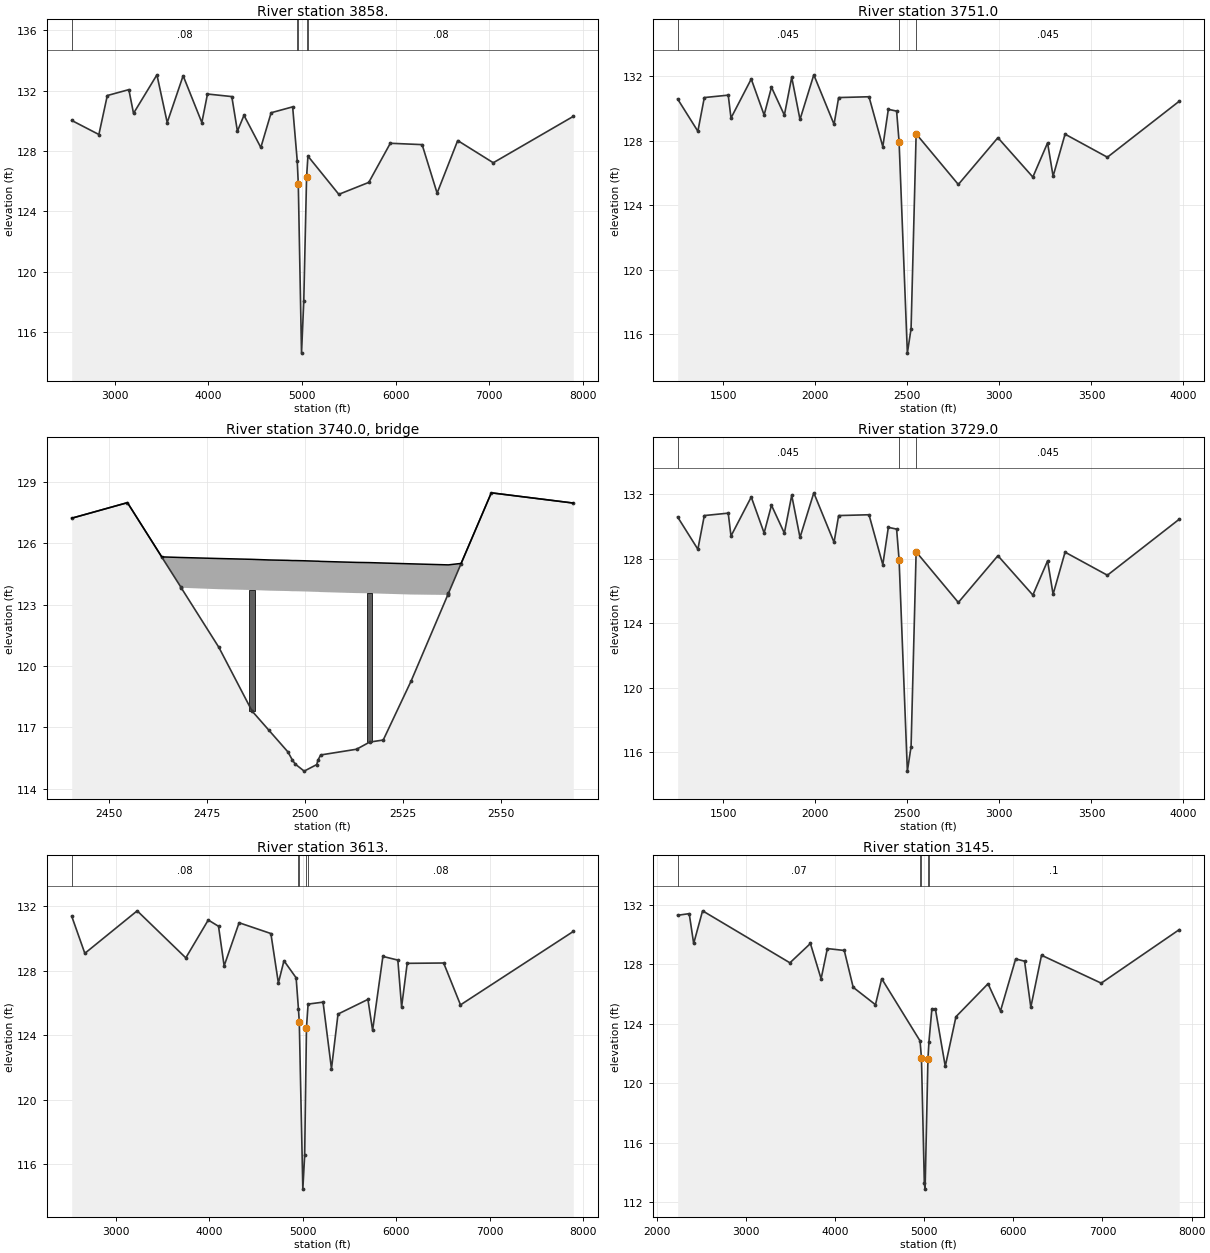
Type RM Length L Ch R = 1 ,3858.   ,163.6,107,40.6
BEGIN DESCRIPTION:
K131-03-00-S02B_PIPELINE - US - XS 4
END DESCRIPTION:
XS GIS Cut Line= 4
      3076523.18      13943823.4      3074156.26     13943433.42
      3074031.81     13943433.42      3071202.32     13943608.56
#Sta/Elev= 30
  2541.2  130.02  2831.2  129.09  2921.2  131.67  3151.2  132.06  3201.2  130.49
  3451.2  133.04  3561.2  129.88  3731.2  132.98  3931.2  129.88  3991.2  131.77
  4251.2   131.6  4311.2  129.31  4381.2  130.36  4561.2  128.23  4671.2  130.53
  4901.2  130.92    4950  127.36  4961.4  125.83 4995.94  114.62    5020  118.05
    5050  126.26  5064.5  127.66  5394.5  125.13  5714.5  125.92  5944.5  128.51
  6284.5  128.42  6444.5  125.21  6664.5  128.69  7044.5  127.22  7899.4  130.29
#Mann= 5 ,-1 , 0
  2541.2     .08       0    4950    .045       0  4961.4     .04       0
    5050    .045       0  5064.5     .08       0
Bank Sta=4961.4,5050
XS Rating Curve= 0
Exp/Cntr=.5,.3

Type RM Length L Ch R = 1 ,3751.0  ,14.2,22,21.4
BEGIN DESCRIPTION:
Upstream Section of Bridge/Culvert/Weir
END DESCRIPTION:
XS GIS Cut Line= 4
      3076516.65     13943718.93      3074124.82     13943262.19
      3074055.49     13943392.77      3071195.79     13943504.08
#Sta/Elev= 30
  1251.3  130.59  1361.3  128.59  1396.3  130.68  1526.3  130.83  1541.3  129.41
  1651.3  131.83  1721.3   129.6  1761.3  131.32  1831.3  129.59  1871.3  131.94
  1916.3  129.321991.301  132.09  2101.3  129.02  2126.3  130.68  2291.3  130.73
2366.301  127.63  2396.3  129.952441.301  129.842454.705  127.952499.754  114.83
2519.905  116.352547.456  128.43 2776.75  125.29 2991.75  128.19 3181.75  125.75
 3261.75  127.87 3291.75   125.8 3356.75  128.41 3586.75  126.983976.949  130.45
#Mann= 3 ,-1 , 0
  1251.3    .045       02454.705     .04       02547.456    .045       0
#XS Ineff= 2 , 0
       0 2468.41  123.82 2536.36       0  123.47
Permanent Ineff=
       F       F
Bank Sta=2454.705,2547.456
XS Rating Curve= 0
Skew Angle= 60
Exp/Cntr=.5,.3

Type RM Length L Ch R = 3 ,3740.0  ,,,
BEGIN DESCRIPTION:
PL1_K131-03-00-S02B
END DESCRIPTION:
Bridge Culvert--1,0,-1,-1, 0
Deck Dist Width WeirC Skew NumUp NumDn MinLoCord MaxHiCord MaxSubmerge Is_Ogee
10,2,2.6,60, 25, 25, , , .95, 0, ,,,
2440.5052454.7052463.456 2468.362468.4052478.0042486.4552490.7542495.6042496.755
2497.5042499.7542502.9552503.2552503.9552513.1042516.4552519.9052527.0052536.355
2536.475 2536.532539.7552547.4562568.354
  127.22  127.98  125.33   125.3   125.3  125.25  125.21  125.18  125.16  125.15
  125.15  125.14  125.12  125.12  125.11  125.06  125.05  125.03  124.99  124.94
  124.94  124.94  125.01  128.46  127.96
  127.22  127.98  125.32  123.84  123.82  123.75  123.71  123.68  123.66  123.65
  123.65  123.64  123.62  123.62  123.61  123.56  123.55  123.53  123.49  123.47
  123.52  123.55     125  128.46  127.96
2440.5052454.7052463.456 2468.362468.4052478.0042486.4552490.7542495.6042496.755
2497.5042499.7542502.9552503.2552503.9552513.1042516.4552519.9052527.0052536.355
2536.475 2536.532539.7552547.4562568.354
  127.22  127.98  125.33   125.3   125.3  125.25  125.21  125.18  125.16  125.15
  125.15  125.14  125.12  125.12  125.11  125.06  125.05  125.03  124.99  124.94
  124.94  124.94  125.01  128.46  127.96
  127.22  127.98  125.32  123.84  123.82  123.75  123.71  123.68  123.66  123.65
  123.65  123.64  123.62  123.62  123.61  123.56  123.55  123.53  123.49  123.47
  123.52  123.55     125  128.46  127.96
Pier Skew, UpSta & Num, DnSta & Num=  ,2486.449, 2 ,2486.449, 2 , 0 , 0 , 0 ,,
     1.3     1.3
  116.73  124.71
     1.3     1.3
  116.73  124.71
Pier Skew, UpSta & Num, DnSta & Num=  ,2516.45, 2 ,2516.45, 2 , 0 , 0 , 0 ,,
     1.3     1.3
  115.25  124.55
     1.3     1.3
  115.25  124.55
BR Coef= 1 , 1 , 1 ,1.25, 0 ,,,.8,0,2,0,
WSPro=,,,, 1 ,,,, 0 ,,,, 0 ,,,,-1 ,-1 ,-1 , 0 , 0 , 0 , 0 , 0
BR U #Sta/Elev= 25
2440.505  127.222454.705  127.982463.456  125.32 2468.36  123.842468.405  123.82
2478.004  120.912486.455   117.82490.754  116.862495.604   115.82496.755   115.4
2497.504   115.22499.754  114.862502.955  115.182503.255  115.392503.955  115.65
2513.104  115.932516.455  116.282519.905  116.382527.005  119.262536.355  123.47
2536.475  123.52 2536.53  123.552539.755     1252547.456  128.462568.354  127.96
BR U #Mann= 3
2440.505    .0452454.705     .042547.456    .045
BR U Banks=2454.705,2547.456
BR D #Sta/Elev= 25
2440.505  127.222454.705  127.982463.456  125.32 2468.36  123.842468.405  123.82
2478.004  120.912486.455   117.82490.754  116.862495.604   115.82496.755   115.4
2497.504   115.22499.754  114.862502.955  115.182503.255  115.392503.955  115.65
2513.104  115.932516.455  116.282519.905  116.382527.005  119.262536.355  123.47
2536.475  123.52 2536.53  123.552539.755     1252547.456  128.462568.354  127.96
BR D #Mann= 3
2440.505    .0452454.705     .042547.456    .045
BR D Banks=2454.705,2547.456
BC Design=,, 0 ,, 0 ,,,,,,

Type RM Length L Ch R = 1 ,3729.0  ,75.2,116,170.1
BEGIN DESCRIPTION:
Downstream Section of Bridge/Culvert/Weir
END DESCRIPTION:
XS GIS Cut Line= 4
      3076520.88     13943714.47      3074114.55     13943254.97
      3074043.69     13943388.42      3071195.49     13943499.29
#Sta/Elev= 30
  1251.3  130.59  1361.3  128.59  1396.3  130.68  1526.3  130.83  1541.3  129.41
  1651.3  131.83  1721.3   129.6  1761.3  131.32  1831.3  129.59  1871.3  131.94
  1916.3  129.321991.301  132.09  2101.3  129.02  2126.3  130.68  2291.3  130.73
2366.301  127.63  2396.3  129.952441.301  129.842454.705  127.952499.754  114.83
2519.905  116.352547.456  128.43 2776.75  125.29 2991.75  128.19 3181.75  125.75
 3261.75  127.87 3291.75   125.8 3356.75  128.41 3586.75  126.983976.949  130.45
#Mann= 3 ,-1 , 0
  1251.3    .045       02454.705     .04       02547.456    .045       0
#XS Ineff= 2 , 0
       0 2468.41  123.82 2536.36       0  123.47
Permanent Ineff=
       F       F
Bank Sta=2454.705,2547.456
XS Rating Curve= 0
Skew Angle= 60
Exp/Cntr=.5,.3

Type RM Length L Ch R = 1 ,3613.   ,461.8,467.98,472.8
BEGIN DESCRIPTION:
K131-03-00-S02B_PIPELINE - DS - XS 1
END DESCRIPTION:
XS GIS Cut Line= 4
      3076507.82      13943603.4      3074131.37     13943174.55
      3074022.85     13943206.41      3071199.13     13943475.78
#Sta/Elev= 30
  2527.1  131.38  2667.1  129.08  3227.1  131.72  3747.1   128.8  3987.1  131.15
  4097.1  130.76  4157.1   128.3  4317.1  130.98  4657.1  130.31  4737.1  127.24
  4797.1  128.62  4927.1  127.56  4951.9  125.62  4960.8  124.83 4998.83  114.44
 5018.44  116.54 5037.75  124.47  5055.1  125.93  5215.1  126.05  5305.1  121.91
  5375.1  125.31  5695.1  126.22  5745.1   124.3  5855.1  128.89  6015.1  128.66
  6055.1  125.75  6115.1  128.46  6505.1  128.48  6685.1  125.88  7891.6  130.44
#Mann= 5 ,-1 , 0
  2527.1     .08       0  4951.9    .045       0  4960.8     .04       0
 5037.75    .045       0  5055.1     .08       0
Bank Sta=4960.8,5037.75
XS Rating Curve= 0
Exp/Cntr=.3,.1

Type RM Length L Ch R = 1 ,3145.   ,89.2,99.1,113.3
BEGIN DESCRIPTION:
K131-03-00-S02E_WEIR- US - XS 4
END DESCRIPTION:
XS GIS Cut Line= 4
      3076592.45      13943542.9       3073994.8     13942734.67
      3073892.83     13942748.44       3071175.9     13943445.91
#Sta/Elev= 30
  2232.2  131.31  2362.2  131.42  2412.2  129.41  2512.2  131.61  3492.2  128.11
  3722.2  129.41  3842.2  127.03  3912.2  129.07  4102.2  128.94  4202.2  126.46
  4452.2  125.29  4522.2  127.04  4952.7  122.85 4968.38   121.7 5000.71  113.25
 5009.28  112.87 5041.04  121.62  5052.7  122.81  5085.6  125.02  5125.6  124.97
  5235.6  121.14  5355.6  124.48  5715.6   126.7  5855.6  124.87  6025.6  128.37
  6125.6  128.22  6195.6  125.12  6315.6  128.62  6985.6  126.74  7860.6  130.34
#Mann= 5 ,-1 , 0
  2232.2     .07       0  4952.7    .045       0 4968.38     .04       0
 5041.04    .045       0  5052.7      .1       0
Bank Sta=4968.38,5041.04
XS Rating Curve= 0
Exp/Cntr=.7,.5