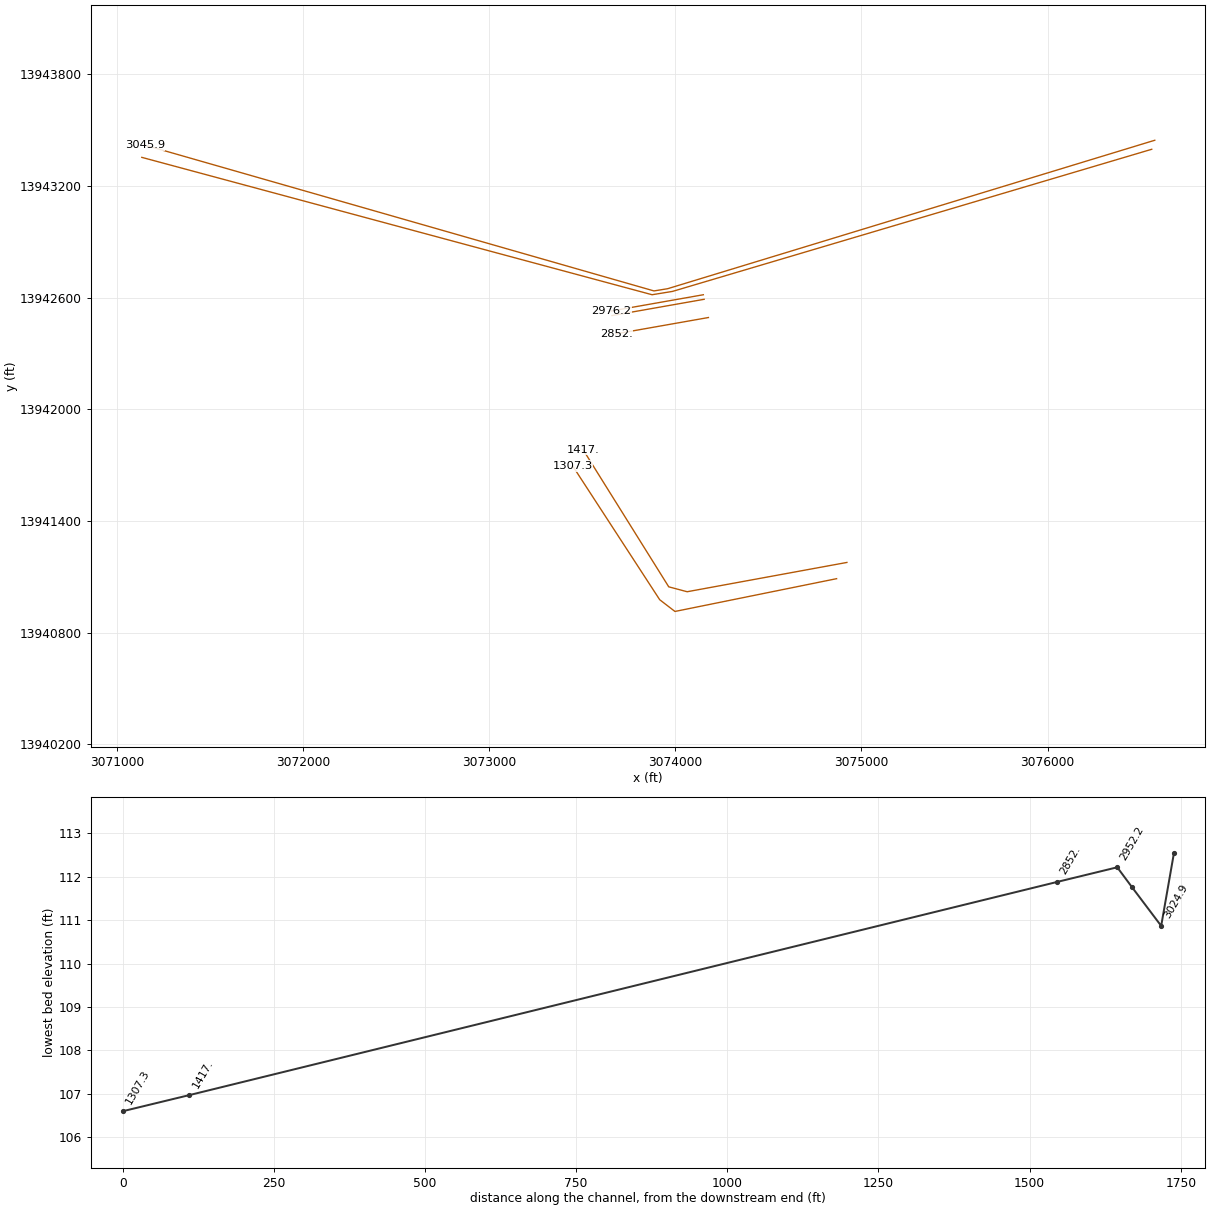
HEC-RAS study K131-03-00.prj: K131-03-00

--- K131-03-00.g01 (geometry) --- (continued)

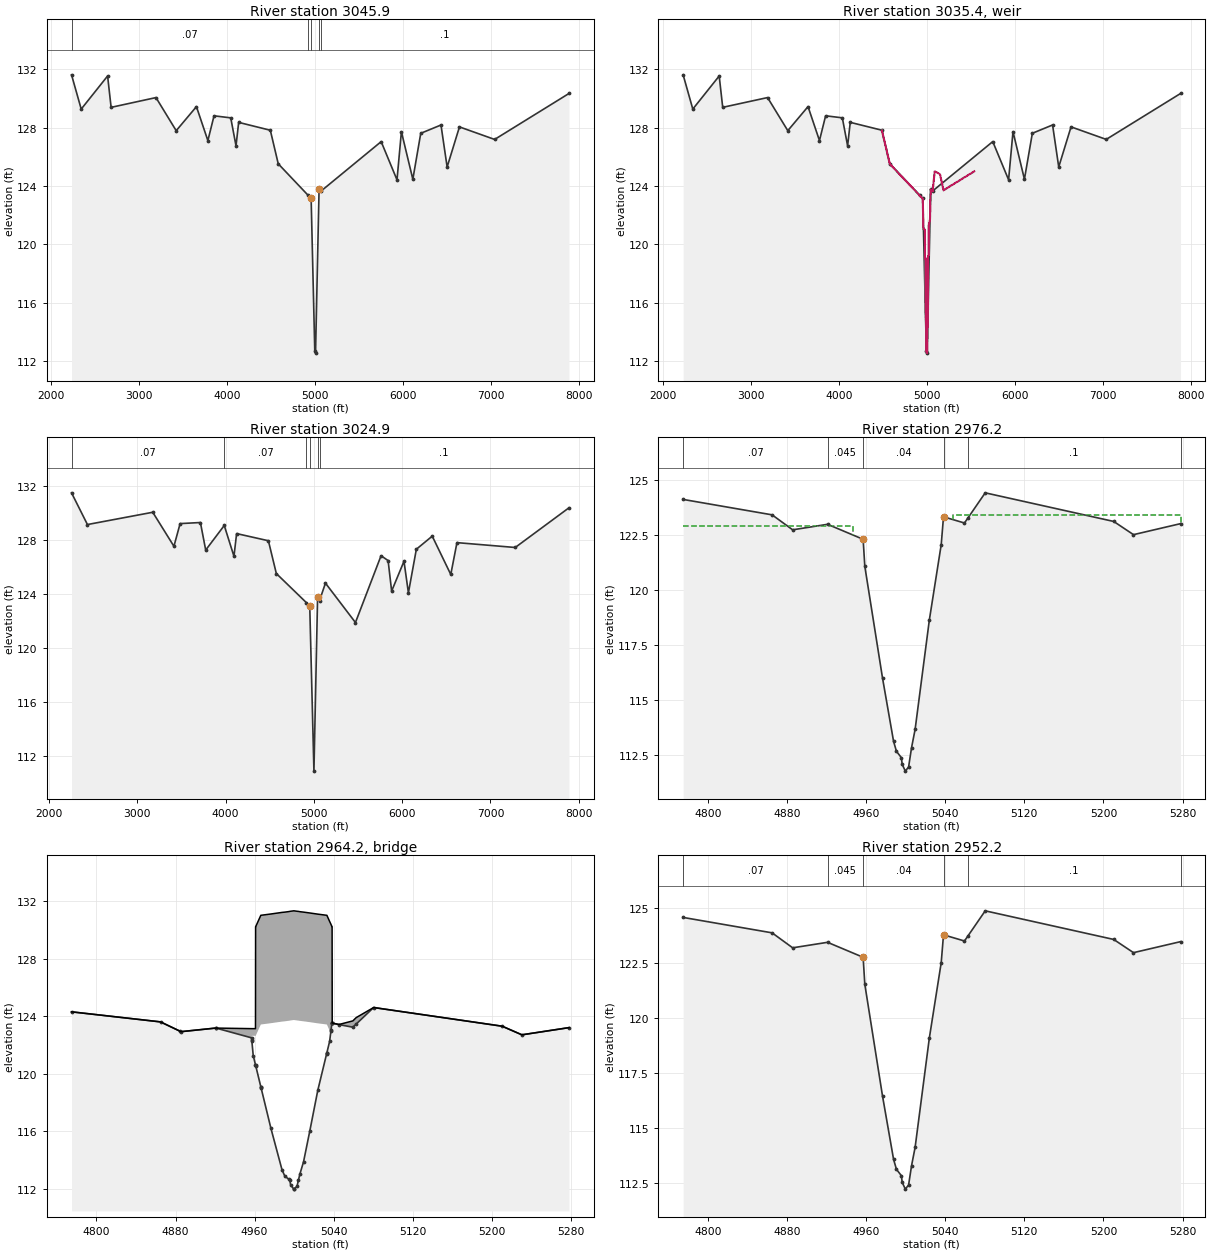
Type RM Length L Ch R = 1 ,3045.9  ,22,21,18.6
BEGIN DESCRIPTION:
Upstream Section of Bridge/Culvert/Weir
END DESCRIPTION:
XS GIS Cut Line= 4
      3076576.13     13943445.02      3073959.35     13942647.55
      3073885.74     13942635.61      3071150.78     13943418.97
#Sta/Elev= 30
  2229.9  131.62  2339.9  129.27  2639.9  131.54  2679.9  129.39  3189.9  130.06
  3419.9  127.79  3649.9  129.44  3779.9  127.11  3849.9  128.81  4039.9  128.67
  4099.9  126.75  4129.9  128.36  4489.9  127.82  4579.9  125.52  4919.5  123.36
  4953.9  123.15  4995.3  112.69    5004  112.54  5044.1  123.77  5066.4  123.65
  5750.1  127.04  5930.1  124.42  5980.1  127.72  6110.1  124.46  6200.1  127.61
  6430.1  128.18  6500.1   125.3  6640.1  128.05  7040.1  127.19    7885  130.34
#Mann= 5 ,-1 , 0
  2229.9     .07       0  4919.5    .045       0  4953.9     .02       0
  5044.1    .045       0  5066.4      .1       0
#XS Ineff= 2 , 0
       0  4943.9     123  5054.1       0  123.63
Permanent Ineff=
       F       F
Bank Sta=4953.9,5044.1
XS Rating Curve= 0
Exp/Cntr=.7,.5

Type RM Length L Ch R = 5 ,3035.4  ,,,
BEGIN DESCRIPTION:
WIER 1055' DS SPRING CYPRESS
Structure ID: K131-03-00-S02E
END DESCRIPTION:
IW Pilot Flow=0
#Inline Weir SE= 30
  4489.9   127.8  4579.9   125.5  4953.9  123.13 4962.49  121.03  4979.1     121
  4979.5  118.99  4986.9  119.06 4987.01  115.38    4993  114.49 4993.11  113.49
  4996.1   113.5  4996.2  112.61    5004  112.53  5004.8  112.69    5005  113.44
  5007.8  113.59    5008  114.48 5010.89   114.5    5011  115.47  5013.9   115.5
  5014.3  119.19  5021.4  119.25  5021.6  121.25 5036.46  121.71  5044.1  123.75
  5066.4  123.63  5090.1     125  5150.1   124.8  5190.1   123.7  5540.1     125
IW Dist,WD,Coef,Skew,MaxSub,Min_El,Is_Ogee,SpillHt,DesHd
10,1,3,0,.95,, 0 ,,,0,0,

Type RM Length L Ch R = 1 ,3024.9  ,46.7,48.7,50
BEGIN DESCRIPTION:
Cross Section FIELD_DS
Located At: WIER 1055' DS SPRING CYPRESS
END DESCRIPTION:
XS GIS Cut Line= 4
      3076559.79     13943396.53      3073985.46     13942633.04
      3073875.71     13942615.15      3071134.44     13943353.12
#Sta/Elev= 30
    2254  131.49    2434  129.14    3174  130.05    3414  127.53    3484  129.21
    3714  129.29    3774  127.25  3984.1  129.07  4094.1  126.79  4124.1  128.47
  4484.1  127.94  4574.1  125.51  4915.2  123.35  4952.6   123.1  5000.1  110.87
  5041.7   123.8  5063.2   123.5  5130.5   124.8  5470.5  121.88  5760.5  126.83
  5840.4  126.47  5880.4  124.21  6020.4  126.42  6070.4  124.08  6160.4  127.31
  6340.4  128.28  6550.4  125.44  6620.4   127.8  7280.4  127.44  7889.2  130.38
#Mann= 6 ,-1 , 0
    2254     .07       0  3984.1     .07       0  4915.2    .045       0
  4952.6     .04       0  5041.7    .045       0  5063.2      .1       0
Bank Sta=4952.6,5041.7
XS Rating Curve= 0
Exp/Cntr=.7,.5

Type RM Length L Ch R = 1 ,2976.2  ,25,24,23
BEGIN DESCRIPTION:
Upstream Section of Bridge/Culvert/Weir
END DESCRIPTION:
XS GIS Cut Line= 4
        3074151.      13942615.1      3074049.57     13942597.18
      3073859.95     13942563.69      3073655.48     13942527.57
#Sta/Elev= 24
  4774.8  124.11  4864.8  123.41  4885.6  122.73  4920.9  122.98  4956.9   122.3
  4958.6  121.07  4976.5     116  4987.7  113.12  4990.6  112.67  4995.6  112.38
  4996.4  112.08  4999.6  111.77  5002.9  111.96  5005.9  112.84  5009.5  113.67
  5023.9  118.64  5035.9  122.06  5038.2  123.32  5059.4  123.04  5062.8  123.26
  5080.4  124.41  5210.4  123.11  5230.4  122.51    5278  123.01
#Mann= 6 ,-1 , 0
  4774.8     .07       0  4920.9    .045       0  4956.9     .04       0
  5038.2    .045       0  5062.8      .1       0    5278     .99       0
#XS Ineff= 2 , 0
       0    4947  122.92    5048       0   123.4
Permanent Ineff=
       F       F
Bank Sta=4956.9,5038.2
XS Rating Curve= 0
Exp/Cntr=.5,.3

Type RM Length L Ch R = 3 ,2964.2  ,,,
BEGIN DESCRIPTION:
METAL FOOT BRIDGE 1650' US TC JESTER
Structure ID: K131-03-00-S02D
END DESCRIPTION:
Bridge Culvert--1,0,-1,-1, 0
Deck Dist Width WeirC Skew NumUp NumDn MinLoCord MaxHiCord MaxSubmerge Is_Ogee
10,4,2.6,0, 47, 47, , , .95, 0, ,,,
  4774.8  4864.8  4884.9  4885.6  4920.7  4920.9  4956.9 4957.11  4957.2  4958.6
 4960.89    4961 4961.11 4966.29  4966.4 4966.51  4976.5  4987.7  4990.6  4994.8
  4995.6  4996.4  4999.6  4999.8  5002.9  5004.3  5005.9  5009.5  5015.9  5023.9
 5032.89    5033 5033.11  5035.9 5037.19  5037.3  5038.2 5038.29  5038.4 5038.51
  5045.4  5059.4  5062.8  5080.4  5210.4  5230.4    5278
   124.3   123.6  122.94  122.92  123.17  123.17  123.13  123.13  123.13  123.13
  123.13  130.23  130.23  131.02  131.02  131.02  131.11  131.22  131.24  131.28
  131.29   131.3  131.33  131.33   131.3  131.29  131.27  131.24  131.18   131.1
  131.02  131.02  131.02  130.59   130.4  130.38  130.24  130.23  130.23  123.52
  123.42  123.67   123.9   124.6   123.3   122.7   123.2
   124.3   123.6  122.94  122.92  123.17  123.17  122.49  122.34  122.63  122.63
  122.63  122.63  122.63  123.42  123.42  123.42  123.51  123.62  123.64  123.68
  123.69   123.7  123.73  123.73   123.7  123.69  123.67  123.64  123.58   123.5
  123.42  123.42  123.42  122.99  122.96  123.02  123.51  123.51  123.51  123.51
  123.41  123.23  123.45   124.6   123.3   122.7   123.2
  4774.8  4864.8  4884.9  4885.6  4920.7  4920.9  4956.9 4957.11  4957.2  4958.6
 4960.89    4961 4961.11 4966.29  4966.4 4966.51  4976.5  4987.7  4990.6  4994.8
  4995.6  4996.4  4999.6  4999.8  5002.9  5004.3  5005.9  5009.5  5015.9  5023.9
 5032.89    5033 5033.11  5035.9 5037.19  5037.3  5038.2 5038.29  5038.4 5038.51
  5045.4  5059.4  5062.8  5080.4  5210.4  5230.4    5278
  124.59  123.89  123.23  123.21  123.46  123.46  123.13  123.13  123.13  123.13
  123.13  130.23  130.23  131.02  131.02  131.02  131.11  131.22  131.24  131.28
  131.29   131.3  131.33  131.33   131.3  131.29  131.27  131.24  131.18   131.1
  131.02  131.02  131.02  130.59   130.4  130.38  130.24  130.23  130.23   123.8
   123.7  123.67   123.9  124.89  123.59  122.99  123.49
  124.59  123.89  123.23  123.21  123.46  123.46  122.78  122.63  122.92  122.92
  122.92  122.92  122.92  123.71  123.71  123.71   123.8  123.91  123.93  123.97
  123.98  123.99  124.02  124.02  123.99  123.98  123.96  123.93  123.87  123.79
  123.71  123.71  123.71  123.28  123.25  123.31   123.8   123.8   123.8   123.8
   123.7  123.52  123.74  124.89  123.59  122.99  123.49
BR Coef= 1 , 1 , 0 ,1.25, 0 ,,,.8,0,2,0,
WSPro=,,,, 1 ,,,, 0 ,,,, 0 ,,,,-1 ,-1 ,-1 , 0 , 0 , 0 , 0 , 0
BR U #Sta/Elev= 47
  4774.8   124.3  4864.8   123.6  4884.9  122.94  4885.6  122.92  4920.7  123.17
  4920.9  123.17  4956.9  122.49 4957.11  122.34  4957.2  122.27  4958.6  121.26
 4960.89  120.61    4961  120.58 4961.11  120.55 4966.29  119.08  4966.4  119.05
 4966.51  119.02  4976.5  116.19  4987.7  113.31  4990.6  112.86  4994.8  112.64
  4995.6  112.57  4996.4  112.27  4999.6  111.96  4999.8  111.97  5002.9  112.15
  5004.3  112.58  5005.9  113.03  5009.5  113.86  5015.9  116.03  5023.9  118.83
 5032.89  121.39    5033  121.42 5033.11  121.45  5035.9  122.25 5037.19  122.96
  5037.3  123.02  5038.2  123.51 5038.29  123.51  5038.4  123.51 5038.51  123.51
  5045.4  123.41  5059.4  123.23  5062.8  123.45  5080.4   124.6  5210.4   123.3
  5230.4   122.7    5278   123.2
BR U #Mann= 6
  4774.8     .07  4920.9    .045  4956.9     .04  5038.2    .045  5062.8      .1
    5278     .99
BR U Banks=4956.9,5038.2
BR D #Sta/Elev= 47
  4774.8  124.59  4864.8  123.89  4884.9  123.23  4885.6  123.21  4920.7  123.46
  4920.9  123.46  4956.9  122.78 4957.11  122.63  4957.2  122.56  4958.6  121.55
 4960.89   120.9    4961  120.87 4961.11  120.84 4966.29  119.37  4966.4  119.34
 4966.51  119.31  4976.5  116.48  4987.7   113.6  4990.6  113.15  4994.8  112.93
  4995.6  112.86  4996.4  112.56  4999.6  112.25  4999.8  112.26  5002.9  112.44
  5004.3  112.87  5005.9  113.32  5009.5  114.15  5015.9  116.32  5023.9  119.12
 5032.89  121.68    5033  121.71 5033.11  121.74  5035.9  122.54 5037.19  123.25
  5037.3  123.31  5038.2   123.8 5038.29   123.8  5038.4   123.8 5038.51   123.8
  5045.4   123.7  5059.4  123.52  5062.8  123.74  5080.4  124.89  5210.4  123.59
  5230.4  122.99    5278  123.49
BR D #Mann= 6
  4774.8     .07  4920.9    .045  4956.9     .04  5038.2    .045  5062.8      .1
    5278     .99
BR D Banks=4956.9,5038.2
BC Design=,, 0 ,, 0 ,,,,,,

Type RM Length L Ch R = 1 ,2952.2  ,101,100.2,99
BEGIN DESCRIPTION:
Downstream Section of Bridge/Culvert/Weir
END DESCRIPTION:
XS GIS Cut Line= 2
       3074155.5     13942590.65      3073659.98     13942503.13
#Sta/Elev= 24
  4774.8  124.56  4864.8  123.86  4885.6  123.18  4920.9  123.43  4956.9  122.75
  4958.6  121.52  4976.5  116.45  4987.7  113.57  4990.6  113.12  4995.6  112.83
  4996.4  112.53  4999.6  112.22  5002.9  112.41  5005.9  113.29  5009.5  114.12
  5023.9  119.09  5035.9  122.51  5038.2  123.77  5059.4  123.49  5062.8  123.71
  5080.4  124.86  5210.4  123.56  5230.4  122.96    5278  123.46
#Mann= 6 ,-1 , 0
  4774.8     .07       0  4920.9    .045       0  4956.9     .04       0
  5038.2    .045       0  5062.8      .1       0    5278     .99       0
#XS Ineff= 2 , 0
       0    4947   121.5    5048       0   121.5
Permanent Ineff=
       F       F
Bank Sta=4956.9,5038.2
XS Rating Curve= 0
Exp/Cntr=.5,.3

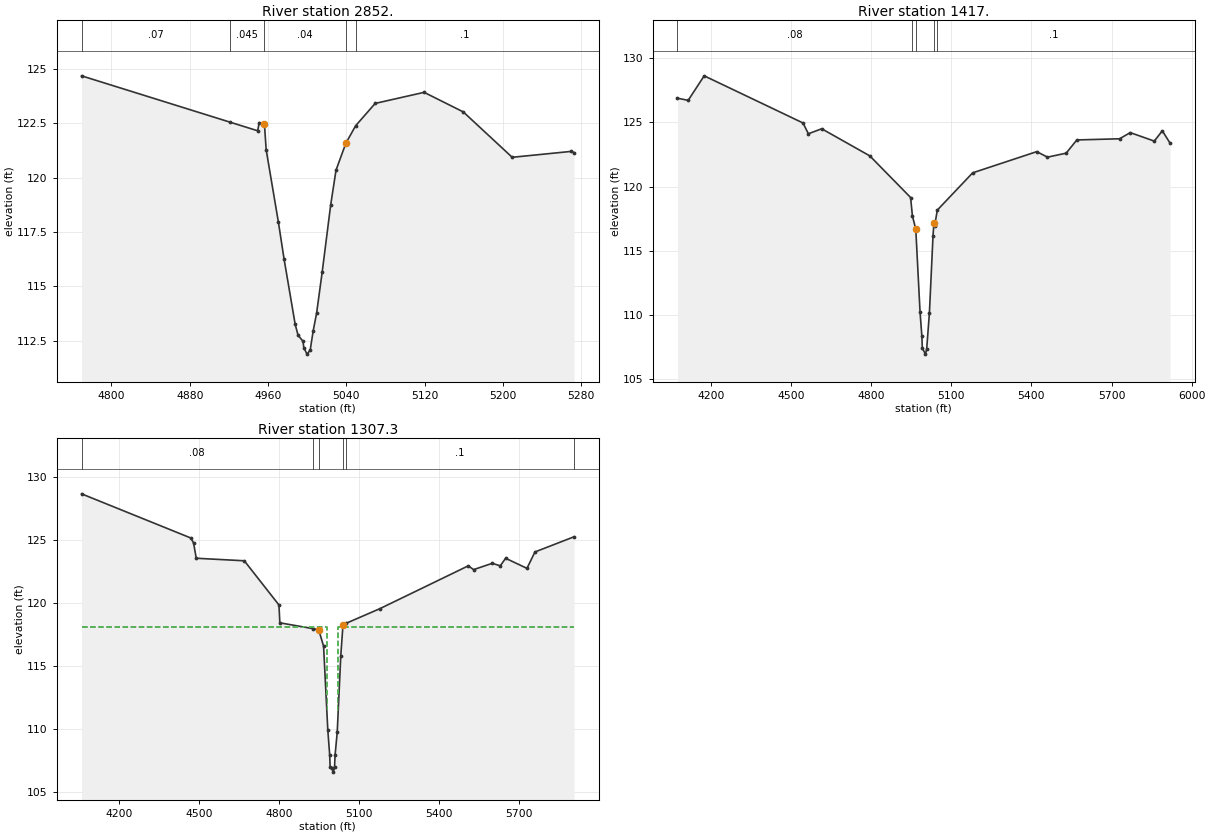
Type RM Length L Ch R = 1 ,2852.   ,1448.6,1435,1419.2
BEGIN DESCRIPTION:
K131-03-00-S02D_METAL FT BRIDGE - DS - XS 1
END DESCRIPTION:
XS GIS Cut Line= 2
      3074178.35      13942492.7      3073682.84     13942405.18
#Sta/Elev= 27
  4769.5  124.69    4921  122.56  4949.5  122.16 4950.93  122.54  4956.4  122.45
 4958.12  121.29 4970.61  117.96 4976.34  116.28 4987.74  113.26 4990.69  112.75
 4995.78  112.47 4996.59  112.18 4999.85  111.88 5003.13  112.07 5006.13  112.94
 5009.71  113.78 5015.32  115.64 5024.06  118.75 5029.51  120.35  5039.5  121.58
  5049.5  122.39  5069.5  123.42  5119.5  123.93  5159.5  123.03  5209.5  120.94
  5269.5  121.21  5272.7  121.16
#Mann= 5 ,-1 , 0
  4769.5     .07       0    4921    .045       0  4956.4     .04       0
  5039.5    .045       0  5049.5      .1       0
Bank Sta=4956.4,5039.5
XS Rating Curve= 0
Exp/Cntr=.3,.1

Type RM Length L Ch R = 1 ,1417.   ,121.3,109.7,90.1
BEGIN DESCRIPTION:
K131-03-00-S1_TC JESTER - US - XS 4
END DESCRIPTION:
XS GIS Cut Line= 4
       3074922.3       13941177.      3074064.04     13941019.61
      3073965.15     13941045.97      3073504.93     13941782.89
#Sta/Elev= 30
  4074.9  126.89  4114.9  126.72  4174.9  128.63  4544.9  124.96  4564.9  124.12
  4614.9  124.51  4794.9   122.4  4947.7  119.16 4954.45  117.73 4967.08  116.69
 4983.04  110.25 4989.93  108.35 4991.61  107.43 5003.43  106.97 5007.95  107.38
 5018.09  110.17 5031.54  116.15 5034.97  117.16  5037.7  116.96  5047.7  118.18
  5180.1  121.08  5420.1  122.73  5460.1   122.3  5530.1  122.61  5570.1  123.64
  5730.1  123.73  5770.1  124.21  5860.1  123.55  5890.1  124.35  5918.9   123.4
#Mann= 5 ,-1 , 0
  4074.9     .08       0 4954.45    .045       0 4967.08     .04       0
 5034.97    .045       0  5047.7      .1       0
Bank Sta=4967.08,5034.97
XS Rating Curve= 0
Exp/Cntr=.5,.3

Type RM Length L Ch R = 1 ,1307.3  ,122,123,124
BEGIN DESCRIPTION:
Upstream Section of Bridge/Culvert/Weir
END DESCRIPTION:
XS GIS Cut Line= 4
      3074866.88     13941089.76      3073998.57     13940913.67
      3073916.54     13940976.77      3073449.43     13941694.73
#Sta/Elev= 30
    4060  128.63    4470  125.13    4480  124.73    4490  123.53    4670  123.33
    4800  119.83  4803.2  118.42  4927.1  117.96  4948.7  117.88  4967.2  116.57
    4983  109.94    4990  107.99  4991.7  107.02  4997.4  106.92  5003.7   106.6
  5008.2  106.99  5010.4  107.97  5018.3  109.75  5031.7  115.83    5040  118.28
  5050.4  118.37  5178.3  119.54  5509.5  122.93  5529.5  122.63  5599.5  123.13
  5629.5  122.93  5649.5  123.53  5729.5  122.73  5759.5  124.03    5906  125.23
#Mann= 6 ,-1 , 0
    4060     .08       0  4927.1    .045       0  4948.7     .04       0
    5040    .045       0  5050.4      .1       0    5906     .99       0
#XS Ineff= 2 , 0
       0  4979.2  118.05  5022.1       0  118.05
Permanent Ineff=
       F       F
Bank Sta=4948.7,5040
XS Rating Curve= 0
Exp/Cntr=.5,.3