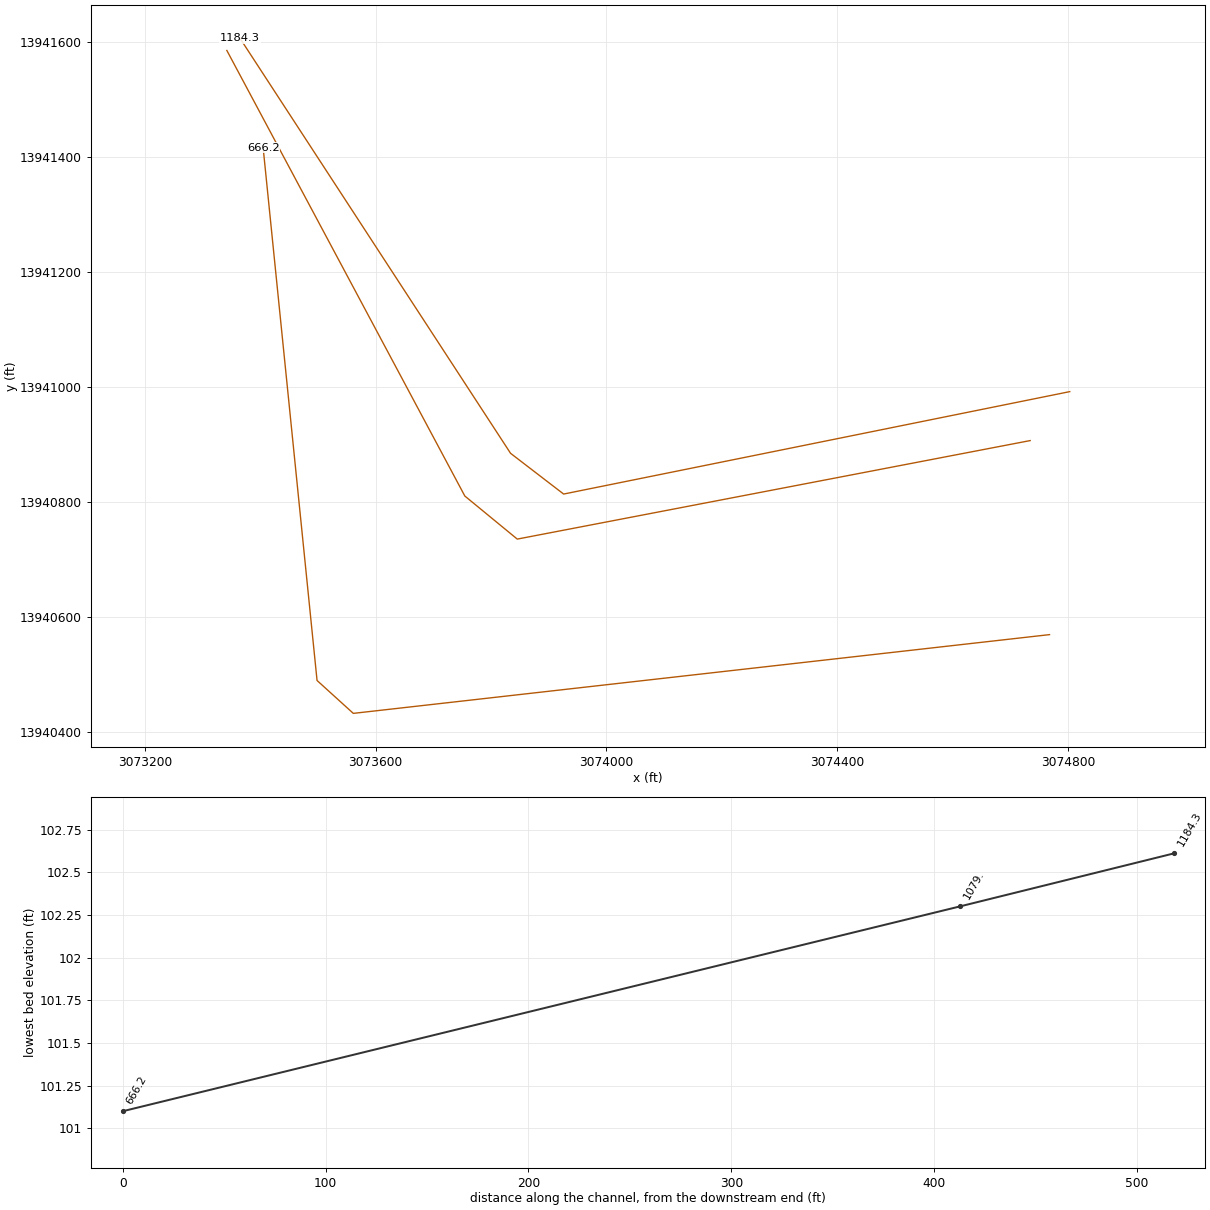
HEC-RAS study K131-03-00.prj: K131-03-00

--- K131-03-00.g01 (geometry) --- (continued)

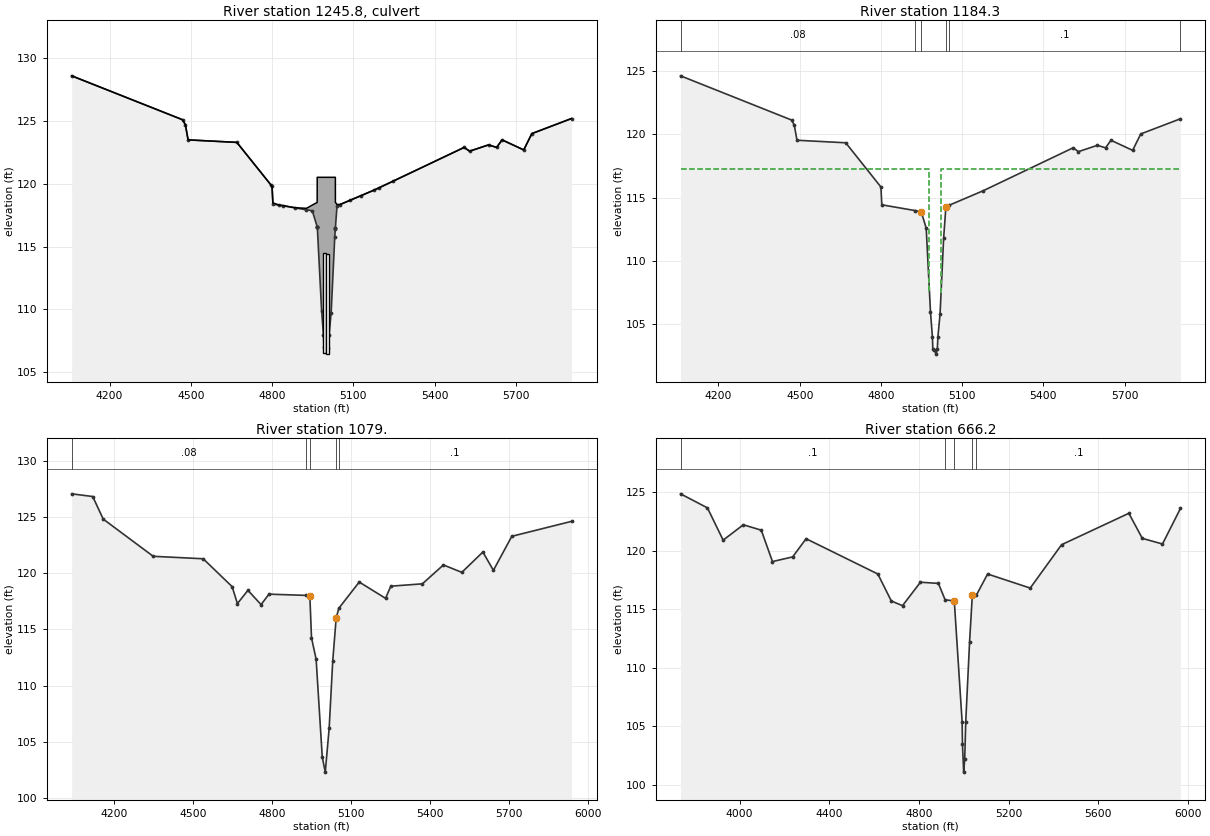
Type RM Length L Ch R = 2 ,1245.8  ,,,
BEGIN DESCRIPTION:
T.C. JESTER   Field Surveyed negative culvert slope
Structure ID: K131-03-00-S1
END DESCRIPTION:
Bridge Culvert--1,0,-1,-1, 0
Deck Dist Width WeirC Skew NumUp NumDn MinLoCord MaxHiCord MaxSubmerge Is_Ogee
10,103,3,0, 44, 44, , , .95, 0, ,,,
    4060    4470    4480    4490    4670  4796.2    4800  4803.2  4826.2  4842.1
  4884.2  4927.1  4948.7 4966.69  4966.8 4966.91  4967.2    4983    4990  4991.7
  4997.4  5003.7  5008.2  5010.4  5018.3  5031.7 5033.79  5033.9 5034.01    5040
  5050.4  5087.7  5128.1  5178.3  5194.2  5247.8  5509.5  5529.5  5599.5  5629.5
  5649.5  5729.5  5759.5    5906
   128.6   125.1   124.7   123.5   123.3  119.91  119.81  118.48  118.31  118.26
   118.1  118.05  118.31  118.52  120.52  120.52  120.52  120.52  120.52  120.52
  120.52  120.52  120.52  120.52  120.52  120.52  120.52  120.52  118.52  118.36
  118.35  118.69  119.06  119.52  119.68  120.22   122.9   122.6   123.1   122.9
   123.5   122.7     124   125.2
   128.6   125.1   124.7   123.5   123.3   119.9   119.8  118.39   118.3  118.25
  118.09  117.93  117.85  116.58  116.57  116.56  116.54  109.91  107.96  106.99
  106.89  106.57  106.96  107.94  109.72   115.8  116.42  116.45  116.48  118.25
  118.34  118.68  119.05  119.51  119.67  120.22   122.9   122.6   123.1   122.9
   123.5   122.7     124   125.2
    4060    4470    4480    4490    4670  4796.2    4800  4803.2  4826.2  4842.1
  4884.2  4927.1  4948.7 4966.69  4966.8 4966.91  4967.2    4983    4990  4991.7
  4997.4  5003.7  5008.2  5010.4  5018.3  5031.7 5033.79  5033.9 5034.01    5040
  5050.4  5087.7  5128.1  5178.3  5194.2  5247.8  5509.5  5529.5  5599.5  5629.5
  5649.5  5729.5  5759.5    5906
   128.6   125.1   124.7   123.5   123.3  119.91  119.81  118.48  118.31  118.26
   118.1  118.05  118.31  118.52  120.52  120.52  120.52  120.52  120.52  120.52
  120.52  120.52  120.52  120.52  120.52  120.52  120.52  120.52  118.52  118.36
  118.35  118.69  119.06  119.52  119.68  120.22   122.9   122.6   123.1   122.9
   123.5   122.7     124   125.2
  124.67  121.17  120.77  119.57  119.37  115.97  115.87  114.46  114.37  114.32
  114.16     114  113.92  112.65  112.64  112.63  112.61  105.98  104.03  103.06
  102.96  102.64  103.03  104.01  105.79  111.87  112.49  112.52  112.55  114.32
  114.41  114.75  115.12  115.58  115.74  116.29  118.97  118.67  119.17  118.97
  119.57  118.77  120.07  121.27
BR Coef= 1 , 1 , 0 ,1.25, 0 ,,,.8,-1,2,0,
WSPro=,,,, 1 ,,,, 0 ,,,, 0 ,,,,-1 ,-1 ,-1 , 0 , 0 , 0 , 0 , 0
Culvert=2,8,11,103,.015,.5,1,8,3,106.49,4994.7,107.76,4994.7,Culvert #1  , 0 ,10
Culvert Bottom n=.015
Culvert=2,8,11,103,.015,.5,1,8,3,106.44,5006.6,107.69,5006.6,Culvert #2  , 0 ,10
Culvert Bottom n=.015
BR U #Sta/Elev= 44
    4060   128.6    4470   125.1    4480   124.7    4490   123.5    4670   123.3
  4796.2   119.9    4800   119.8  4803.2  118.39  4826.2   118.3  4842.1  118.25
  4884.2  118.09  4927.1  117.93  4948.7  117.85 4966.69  116.58  4966.8  116.57
 4966.91  116.56  4967.2  116.54    4983  109.91    4990  107.96  4991.7  106.99
  4997.4  106.89  5003.7  106.57  5008.2  106.96  5010.4  107.94  5018.3  109.72
  5031.7   115.8 5033.79  116.42  5033.9  116.45 5034.01  116.48    5040  118.25
  5050.4  118.34  5087.7  118.68  5128.1  119.05  5178.3  119.51  5194.2  119.67
  5247.8  120.22  5509.5   122.9  5529.5   122.6  5599.5   123.1  5629.5   122.9
  5649.5   123.5  5729.5   122.7  5759.5     124    5906   125.2
BR U #Mann= 5
    4060     .08  4927.1    .045  4948.7     .04    5040    .045  5050.4      .1
BR U Banks=4948.7,5040
BR D #Sta/Elev= 44
    4060   128.6    4470   125.1    4480   124.7    4490   123.5    4670   123.3
  4796.2   119.9    4800   119.8  4803.2  118.39  4826.2   118.3  4842.1  118.25
  4884.2  118.09  4927.1  117.93  4948.7  117.85 4966.69  116.58  4966.8  116.57
 4966.91  116.56  4967.2  116.54    4983  109.91    4990  107.96  4991.7  106.99
  4997.4  106.89  5003.7  106.57  5008.2  106.96  5010.4  107.94  5018.3  109.72
  5031.7   115.8 5033.79  116.42  5033.9  116.45 5034.01  116.48    5040  118.25
  5050.4  118.34  5087.7  118.68  5128.1  119.05  5178.3  119.51  5194.2  119.67
  5247.8  120.22  5509.5   122.9  5529.5   122.6  5599.5   123.1  5629.5   122.9
  5649.5   123.5  5729.5   122.7  5759.5     124    5906   125.2
BR D #Mann= 5
    4060     .08  4927.1    .045  4948.7     .04    5040    .045  5050.4      .1
BR D Banks=4948.7,5040
BC Design=,, 0 ,, 0 ,,,,,,

Type RM Length L Ch R = 1 ,1184.3  ,110.3,105.3,104
BEGIN DESCRIPTION:
Downstream Section of Bridge/Culvert/Weir
END DESCRIPTION:
XS GIS Cut Line= 4
       3074803.3     13940992.02      3073926.05     13940814.12
      3073834.08     13940884.86      3073365.11     13941605.69
#Sta/Elev= 30
    4060  124.64    4470  121.14    4480  120.74    4490  119.54    4670  119.34
    4800  115.84  4803.2  114.43  4927.1  113.97  4948.7  113.89  4967.2  112.58
    4983  105.95    4990     104  4991.7  103.03  4997.4  102.93  5003.7  102.61
  5008.2     103  5010.4  103.98  5018.3  105.76  5031.7  111.84    5040  114.29
  5050.4  114.38  5178.3  115.55  5509.5  118.94  5529.5  118.64  5599.5  119.14
  5629.5  118.94  5649.5  119.54  5729.5  118.74  5759.5  120.04    5906  121.24
#Mann= 6 ,-1 , 0
    4060     .08       0  4927.1    .045       0  4948.7     .04       0
    5040    .045       0  5050.4      .1       0    5906     .99       0
#XS Ineff= 2 , 0
       0  4979.2  117.25  5022.1       0  117.25
Permanent Ineff=
       F       F
Bank Sta=4948.7,5040
XS Rating Curve= 0
Exp/Cntr=.5,.3

Type RM Length L Ch R = 1 ,1079.   ,414,412.8,410.5
BEGIN DESCRIPTION:
K131-03-00-S1_TC JESTER - DS - XS 1
END DESCRIPTION:
XS GIS Cut Line= 4
      3074734.74       13940907.      3073845.67     13940735.89
      3073754.78     13940810.69      3073342.26     13941584.64
#Sta/Elev= 30
  4038.8  127.07  4118.8  126.83  4158.8  124.82  4348.8  121.51  4538.8  121.29
  4648.8  118.81  4668.8   117.3  4708.8  118.48  4758.8  117.21  4788.8  118.14
    4931  118.03  4944.2  117.99 4950.47  114.26 4968.07  112.35 4991.39  103.64
 5002.81   102.3  5017.6   106.2 5031.18  112.18  5044.2     116  5054.2  116.88
  5131.9  119.22  5231.9  117.77  5251.9  118.85  5371.9  119.06  5451.9  120.74
  5521.9  120.08  5601.9  121.89  5641.9  120.26  5711.9  123.29  5938.9  124.62
#Mann= 5 ,-1 , 0
  4038.8     .08       0    4931    .045       0  4944.2     .04       0
  5044.2    .045       0  5054.2      .1       0
Bank Sta=4944.2,5044.2
XS Rating Curve= 0
Exp/Cntr=.3,.1

Type RM Length L Ch R = 1 ,666.2   ,0,0,0
BEGIN DESCRIPTION:
Cross Section K131-03-00-X01
END DESCRIPTION:
XS GIS Cut Line= 4
      3074768.28     13940569.95      3073561.47     13940433.16
      3073498.63     13940490.28      3073405.19      13941415.5
#Sta/Elev= 30
  3736.5  124.84  3856.5  123.64  3926.5  120.89  4016.5   122.2  4096.5  121.74
  4146.5  119.06  4236.5  119.46  4296.5  121.01  4616.5     118  4676.5   115.7
  4726.5   115.3  4806.5   117.3  4886.5   117.2  4916.5   115.8  4957.4   115.7
  4992.4  105.38  4993.9  103.47  4999.3   101.1  5003.9  102.18  5008.5   105.4
  5025.7  112.24    5038  116.25    5056   116.2    5106     118    5296   116.8
    5436   120.5    5736  123.18    5796  121.04    5886  120.56    5966  123.59
#Mann= 5 ,-1 , 0
  3736.5      .1       0  4916.5    .045       0  4957.4     .04       0
    5038    .045       0    5056      .1       0
Bank Sta=4957.4,5038
XS Rating Curve= 0
Exp/Cntr=.3,.1

Chan Stop Cuts=-1